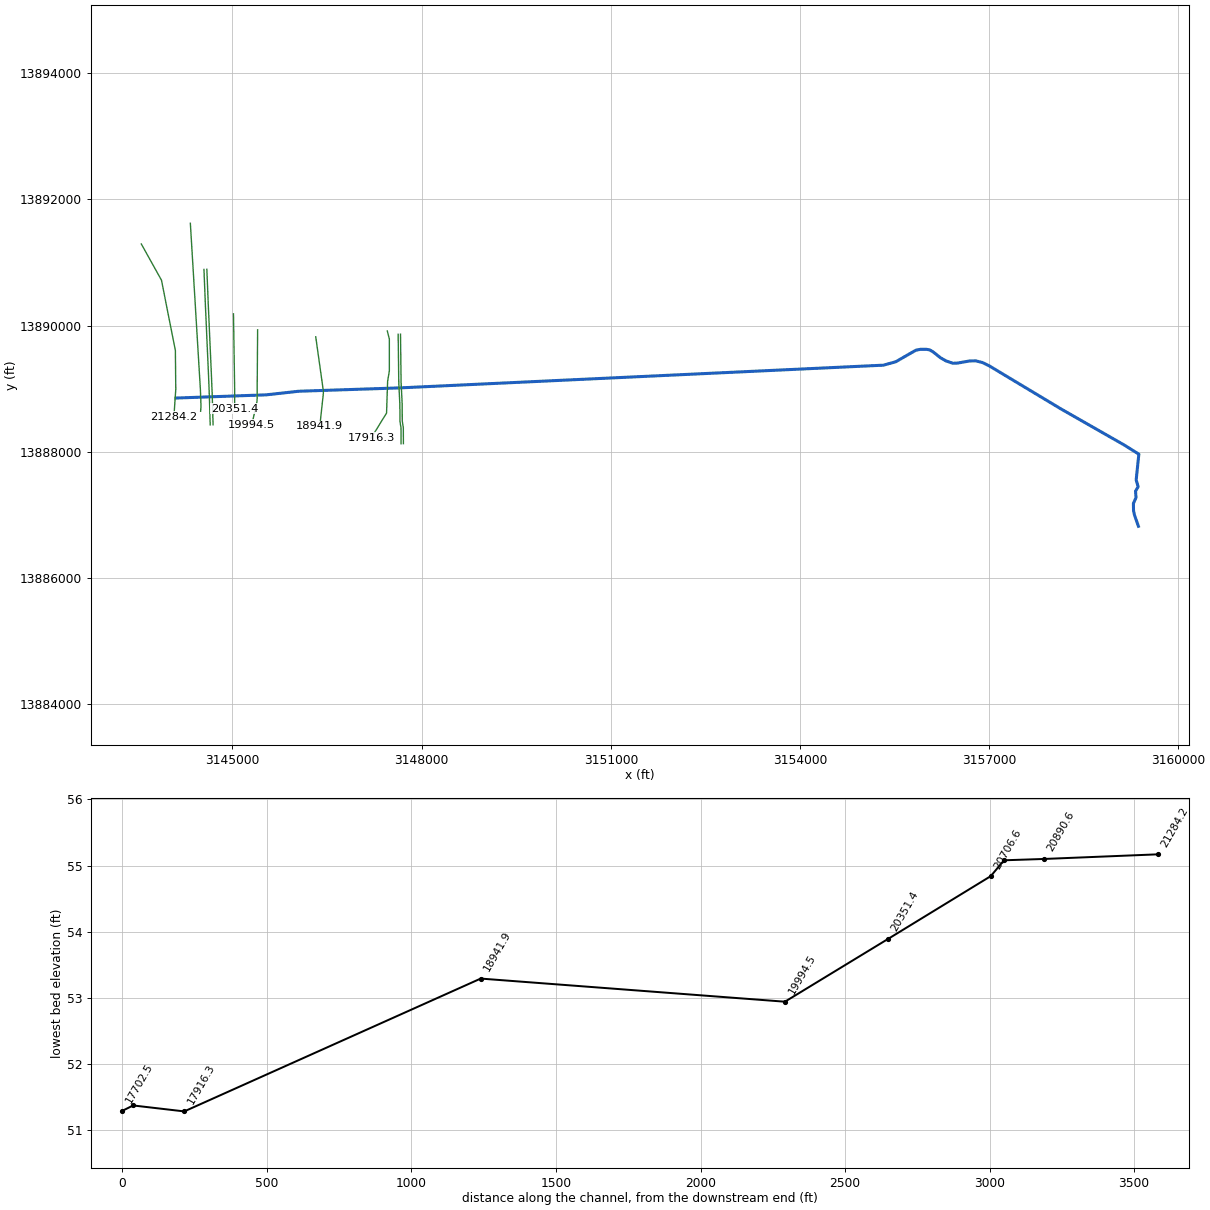
--- P126-00-00.PRJ (project) ---

Proj Title=P126-00-00
Current Plan=p02
Default Exp/Contr=.3,.1
English Units
Geom File=g01
Flow File=f02
Flow File=f01
Plan File=p02
Plan File=p01
Y Axis Title=Elevation
X Axis Title(PF)=Main Channel Distance
X Axis Title(XS)=Station
BEGIN DESCRIPTION:
Greens Bayou Watershed
Tributary 14.82 To Greens Bayou
HCFCD Unit P126-00-00
Flood Hazard Model
10, 2, 1, 0.2% Event
Filename P126-00-00.prj
Prepared by:  Watershed Concepts  Date:
Reviewed by:                      Date:
STATUS FINAL
END DESCRIPTION:
DSS Export Rating Curves= 0
DSS Export Rating Curve Sorted= 0
DSS Export Volume Flow Curves= 0
DXF OffsetX= 0
DXF OffsetY= 0
DXF ScaleX= 1
DXF ScaleY= 10

--- P126-00-00.p02 (plan) ---

Plan Title=Floodway
Version=Version 3.0.1  Mar 2001
Short Identifier=Floodway0607
Geom File=g01
Flow File=f02
Subcritical Flow
K Sum by GR= 0
Std Step Tol= 0.01
Critical Tol= 0.01
Num of Std Step Trials= 20
Max Error Tol= 0.3
Flow Tol Ratio= 0.001
Split Flow NTrial= 30
Split Flow Tol= 0.02
Split Flow Ratio= 0.02
Log Output Level= 0
Friction Slope Method= 1
Unsteady Friction Slope Method= 2
Parabolic Critical Depth
Global Vel Dist= 0 , 0 , 0
Global Log Level= 0
CheckData=True
Encroach Param=-1 ,0,0, 2
Encroach River=P126-00-00
Encroach Reach=Reach - 1
Encroach Node=21284.2
       1  4952.4  5018.4
Encroach Node=20890.6
       1    4970  5018.4
Encroach Node=20752.6
       1    4970    5025
Encroach Node=20729.6
       1    4970    5025
Encroach Node=20706.6
       1    4970    5025
Encroach Node=20351.4
       1  4963.1  5021.5
Encroach Node=19994.5
       1  4979.2  5021.5
Encroach Node=18941.9
       1  4977.9  5022.5
Encroach Node=17916.3
       1    4750    5030
Encroach Node=17739.5
       1    4650    5040
Encroach Node=17721.0
       1    4650    5040
Encroach Node=17702.5
       1    4650    5040
Encroach Node=17519.2
       1    4728    5030
Encroach Node=16944.5
       1    4747    5040
Encroach Node=16316.6
       1    4937    5027
Encroach Node=15942.6
       1    4884    5030
Encroach Node=15838.7
       1    4884    5030
Encroach Node=15815.7
       1    4884    5030
Encroach Node=15792.7
       1    4884    5030
Encroach Node=15415.3
       1    4966    5024
Encroach Node=14842.8
       1    4930  5021.2
Encroach Node=13654.3
       1    4958  5022.5
Encroach Node=12737.3
       1    4400  5022.2
Encroach Node=11789.0
       1    4470    5044
Encroach Node=11225.3
       1    4500    5150
Encroach Node=11139.8
       1    4500    5200
Encroach Node=11112.3
       1    4500    5200
Encroach Node=11084.8
       1    4500    5200
Encroach Node=10856.2
       1    4150    5425
Encroach Node=10074.5
       1    4550    5047
Encroach Node=9410.0
       1    4968    5100
Encroach Node=9172.5
       1    4975    5025
Encroach Node=9150.1
       1    4975    5025
Encroach Node=9127.7
       1    4975    5025
Encroach Node=8662.2
       1    4925    5075
Encroach Node=8135.9
       1  4978.6  5025.6
Encroach Node=7243.2
       1    4972  5029.4
Encroach Node=6798.4
       1  4935.8  5045.8
Encroach Node=6368.8
       1  4932.7  5072.7
Encroach Node=5960.5
       1  4928.6  5030.3
Encroach Node=5364.3
       1  4980.3  5024.4
Encroach Node=4406.7
       1  4959.5  5035.8
Encroach Reach=P126-00-00_0044
Encroach Node=21284.2
       1  4952.4  5018.4
Encroach Node=20890.6
       1    4970  5018.4
Encroach Node=20752.6
       1    4970    5025
Encroach Node=20729.6
       1    4970    5025
Encroach Node=20706.6
       1    4970    5025
Encroach Node=20351.4
       1  4963.1  5021.5
Encroach Node=19994.5
       1  4979.2  5021.5
Encroach Node=18941.9
       1  4977.9  5022.5
Encroach Node=17916.3
       1    4750    5030
Encroach Node=17739.5
       1    4650    5040
Encroach Node=17721.0
       1    4650    5040
Encroach Node=17702.5
       1    4650    5040
Encroach Node=17519.2
       1    4728    5030
Encroach Node=16944.5
       1    4747    5040
Encroach Node=16316.6
       1    4937    5027
Encroach Node=15942.6
       1    4884    5030
Encroach Node=15838.7
       1    4884    5030
Encroach Node=15815.7
       1    4884    5030
Encroach Node=15792.7
       1    4884    5030
Encroach Node=15415.3
       1    4966    5024
Encroach Node=14842.8
       1    4930  5021.2
Encroach Node=13654.3
       1    4958  5022.5
Encroach Node=12737.3
       1    4400  5022.2
Encroach Node=11789.0
       1    4470    5044
Encroach Node=11225.3
       1    4500    5150
Encroach Node=11139.8
       1    4500    5200
Encroach Node=11112.3
       1    4500    5200
Encroach Node=11084.8
       1    4500    5200
Encroach Node=10856.2
       1    4150    5425
Encroach Node=10074.5
       1    4550    5047
Encroach Node=9410.0
       1    4968    5100
Encroach Node=9172.5
       1    4975    5025
Encroach Node=9150.1
       1    4975    5025
Encroach Node=9127.7
       1    4975    5025
Encroach Node=8662.2
       1    4925    5075
Encroach Node=8135.9
       1  4978.6  5025.6
Encroach Node=7243.2
       1    4972  5029.4
Encroach Node=6798.4
       1  4935.8  5045.8
Encroach Node=6368.8
       1  4932.7  5072.7
Encroach Node=5960.5
       1  4928.6  5030.3
Encroach Node=5364.3
       1  4980.3  5024.4
Encroach Node=4406.7
       1  4959.5  5035.8
Computation Interval=1HOUR
Output Interval=1HOUR
Run HTab= 0
Run UNet= 0
Run PostProcess= 0
UNET Theta= 1
UNET ZTol= 0.02
UNET ZSATol= 0.1
UNET MxIter= 20
UNET MaxInSteps= 20
UNET DtIC= 0
UNET DtMin= 0
UNET MaxCRTS= 20
UNET WFStab= 2
UNET SFStab= 1
UNET WFX= 1
UNET SFX= 1
UNET Convert EG Bridges=-1
UNET Use Existing IB Tables=-1
Instantaneous Interval=1HOUR
Write IC File= 0
Write Velocity= 0
Write Detailed= 0

--- P126-00-00.p01 (plan) ---

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Plan Title=FEMA Effective June 2007
Short Identifier=FEMAeff0607
Geom File=g01
Flow File=f01
Encroach Param=-1 ,0,0, 0

--- P126-00-00.f02 (steady flow) ---

Flow Title= Floodway
Number of Profiles= 2
Profile Names=1PCT_100yr, 1PCTFloodway_100yrFW
River Rch & RM=P126-00-00,P126-00-00_0044,21284.2
     481     481
River Rch & RM=P126-00-00,P126-00-00_0044,20890.6
     500     500
River Rch & RM=P126-00-00,P126-00-00_0044,20752.6
     541     541
River Rch & RM=P126-00-00,P126-00-00_0044,20351.4
     585     585
River Rch & RM=P126-00-00,P126-00-00_0044,19994.5
     736     736
River Rch & RM=P126-00-00,P126-00-00_0044,18941.9
     773     773
River Rch & RM=P126-00-00,P126-00-00_0044,17916.3
     788     788
River Rch & RM=P126-00-00,P126-00-00_0044,17519.2
     810     810
River Rch & RM=P126-00-00,P126-00-00_0044,16944.5
     834     834
River Rch & RM=P126-00-00,P126-00-00_0044,16316.6
     850     850
River Rch & RM=P126-00-00,P126-00-00_0044,15942.6
     856     856
River Rch & RM=P126-00-00,P126-00-00_0044,15838.7
     871     871
River Rch & RM=P126-00-00,P126-00-00_0044,15415.3
     895     895
River Rch & RM=P126-00-00,P126-00-00_0044,14842.8
     948     948
River Rch & RM=P126-00-00,P126-00-00_0044,13654.3
     991     991
River Rch & RM=P126-00-00,P126-00-00_0044,12737.3
    1037    1037
River Rch & RM=P126-00-00,P126-00-00_0044,11789
    1065    1065
River Rch & RM=P126-00-00,P126-00-00_0044,11225.3
    1125    1125
River Rch & RM=P126-00-00,P126-00-00_0044,10074.5
    1204    1204
River Rch & RM=P126-00-00,P126-00-00_0044,8662.2
    1289    1289
River Rch & RM=P126-00-00,P126-00-00_0044,7243.2
    1371    1371
River Rch & RM=P126-00-00,P126-00-00_0044,5960.5
    1477    1477
Boundary for River Rch & Prof#=P126-00-00,P126-00-00_0044, 1
Up Type= 0
Dn Type= 3
Dn Slope= 0.00540
Boundary for River Rch & Prof#=P126-00-00,P126-00-00_0044, 2
Up Type= 0
Dn Type= 1
Dn Known WS=39.84

--- P126-00-00.f01 (steady flow) ---

Flow Title= FEMA Effective June 2007
Number of Profiles= 4
Profile Names=10PCT_10yr, 2PCT_50yr, 1PCT_100yr, 0.2PCT_500yr
River Rch & RM=P126-00-00,P126-00-00_0044,21284.2
     268     408     481     696
River Rch & RM=P126-00-00,P126-00-00_0044,20890.6
     279     425     500     724
River Rch & RM=P126-00-00,P126-00-00_0044,20752.6
     301     459     541     783
River Rch & RM=P126-00-00,P126-00-00_0044,20351.4
     325     497     585     846
River Rch & RM=P126-00-00,P126-00-00_0044,19994.5
     410     625     736    1065
River Rch & RM=P126-00-00,P126-00-00_0044,18941.9
     446     661     773    1112
River Rch & RM=P126-00-00,P126-00-00_0044,17916.3
     461     676     788    1131
River Rch & RM=P126-00-00,P126-00-00_0044,17519.2
     483     697     810    1159
River Rch & RM=P126-00-00,P126-00-00_0044,16944.5
     509     722     834    1191
River Rch & RM=P126-00-00,P126-00-00_0044,16316.6
     525     736     850    1210
River Rch & RM=P126-00-00,P126-00-00_0044,15942.6
     531     743     856    1217
River Rch & RM=P126-00-00,P126-00-00_0044,15838.7
     548     758     871    1237
River Rch & RM=P126-00-00,P126-00-00_0044,15415.3
     575     782     895    1268
River Rch & RM=P126-00-00,P126-00-00_0044,14842.8
     634     835     948    1333
River Rch & RM=P126-00-00,P126-00-00_0044,13654.3
     684     877     991    1386
River Rch & RM=P126-00-00,P126-00-00_0044,12737.3
     740     924    1037    1443
River Rch & RM=P126-00-00,P126-00-00_0044,11789
     756     948    1065    1484
River Rch & RM=P126-00-00,P126-00-00_0044,11225.3
     790    1000    1125    1571
River Rch & RM=P126-00-00,P126-00-00_0044,10074.5
     835    1067    1204    1685
River Rch & RM=P126-00-00,P126-00-00_0044,8662.2
     882    1139    1289    1808
River Rch & RM=P126-00-00,P126-00-00_0044,7243.2
     927    1209    1371    1926
River Rch & RM=P126-00-00,P126-00-00_0044,5960.5
     985    1298    1477    2081
Boundary for River Rch & Prof#=P126-00-00,P126-00-00_0044, 1
Up Type= 0
Dn Type= 3
Dn Slope= 0.00540
Boundary for River Rch & Prof#=P126-00-00,P126-00-00_0044, 2
Up Type= 0
Dn Type= 3
Dn Slope= 0.00540
Boundary for River Rch & Prof#=P126-00-00,P126-00-00_0044, 3
Up Type= 0
Dn Type= 3
Dn Slope= 0.00540
Boundary for River Rch & Prof#=P126-00-00,P126-00-00_0044, 4
Up Type= 0
Dn Type= 3
Dn Slope= 0.00540

--- P126-00-00.g01 (geometry) ---

Geom Title=P126-00-00 June 2007
Version=Version 3.0.1  Mar 2001

River Reach=P126-00-00      ,P126-00-00_0044
Reach XY= 30
      3144102.21     13888853.37      3145533.75       13888904.
      3146049.25       13888961.      3147659.42      13889014.5
      3155323.13     13889374.21       3155518.5       13889428.
       3155837.5       13889611.       3155913.5       13889626.
      3156003.25       13889626.        3156057.       13889616.
      3156106.75       13889588.        3156230.       13889491.
       3156317.5       13889441.        3156423.       13889405.
      3156498.75       13889407.       3156689.5       13889441.
      3156786.25       13889443.       3156891.5       13889417.
        3157001.       13889364.       3158137.5       13888682.
      3159134.36       13888114.      3159374.77     13887964.19
      3159332.13     13887556.16       3159363.6     13887447.78
      3159321.73     13887377.99      3159330.11      13887277.5
      3159288.24      13887182.6      3159290.19     13887072.28
      3159305.17     13887000.37        3159368.       13886822.

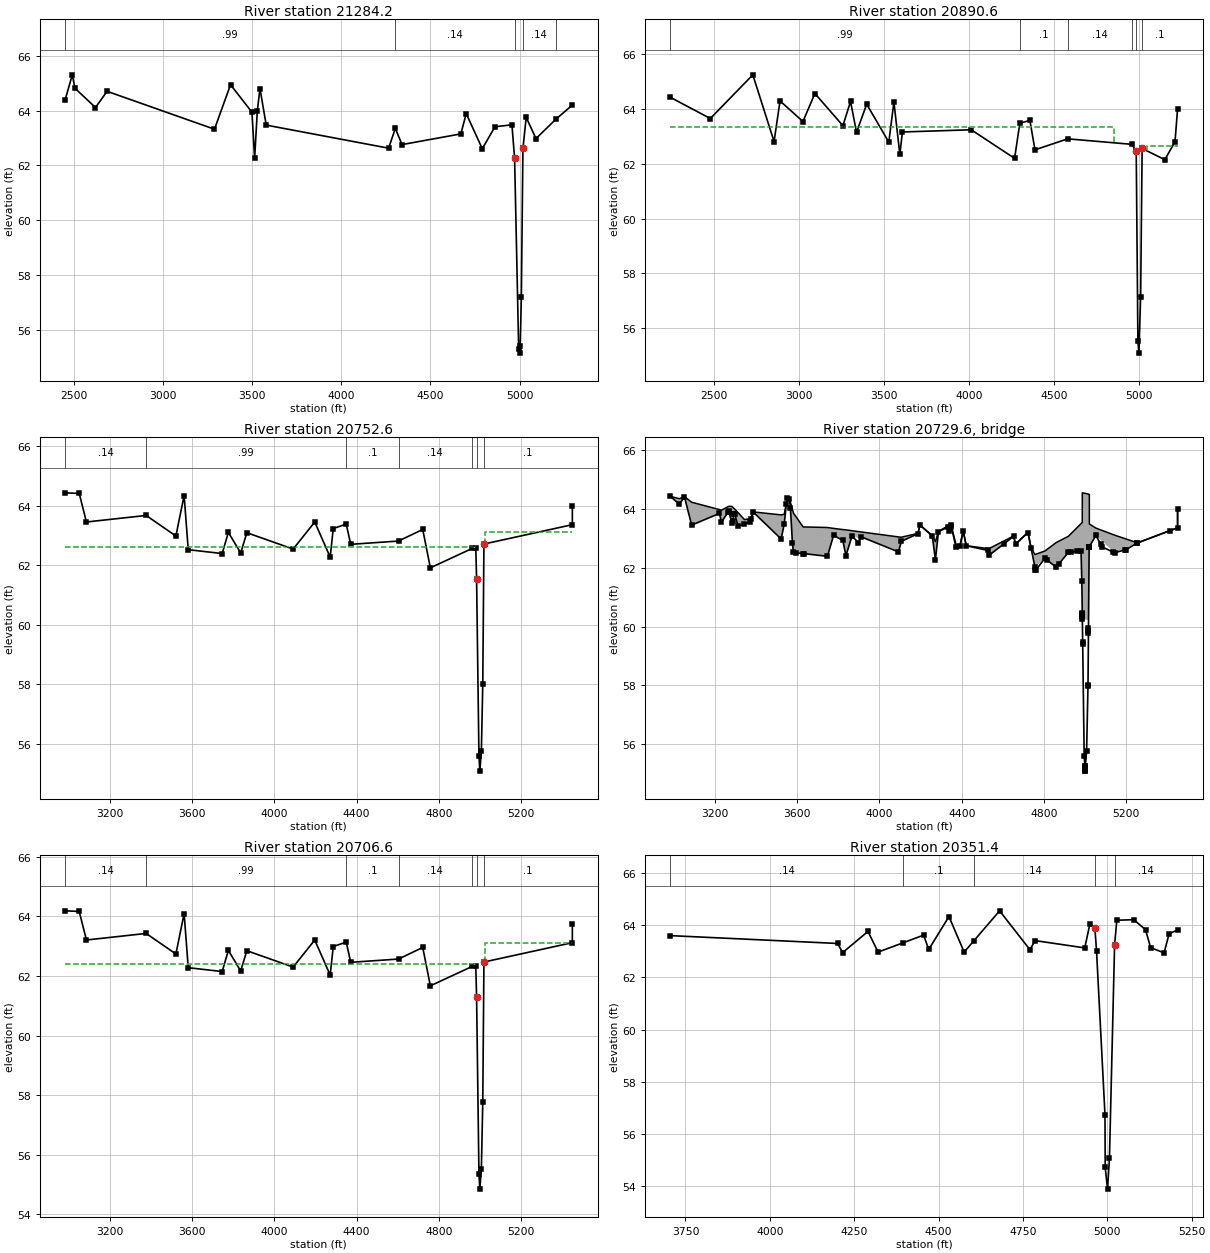
Type RM Length L Ch R = 1 ,21284.2 ,378,393.6,396
BEGIN DESCRIPTION:
Cross Section 21284.2-Interpolated
END DESCRIPTION:
XS GIS Cut Line= 5
      3143553.53     13891295.11      3143873.47     13890721.43
      3144094.12     13889607.16      3144100.39     13888990.96
      3144070.79     13888558.35
#Sta/Elev= 30
  2452.7   64.39  2492.7    65.3  2507.7   64.81  2622.7   64.11  2687.7    64.7
  3289.6   63.32  3379.6   64.94  3499.6   63.94  3514.6   62.26  3529.6   63.98
  3544.6    64.8  3579.6   63.47  4265.5   62.63  4303.4   63.35  4340.5   62.76
  4670.5   63.15  4700.5   63.89  4790.5   62.61  4861.7   63.41  4956.7   63.48
  4971.7   62.27  4994.5   55.33  4999.5   55.17  5003.3   55.43  5009.5   57.22
  5018.4   62.62  5036.7   63.75  5091.7   62.98  5202.3   63.68  5295.4    64.2
#Mann= 5 , 1 , 0
  2452.7     .99       0  4303.4     .14       0  4971.7     .04       0
  5018.4     .14       0  5202.3      .1       0
#XS Ineff= 2 , 0
       0  4721.2    63.5  5202.4       0    63.4
Permanent Ineff=
       F       F
Bank Sta=4971.7,5018.4
XS Rating Curve= 0
Exp/Cntr=.3,.1

Type RM Length L Ch R = 1 ,20890.6 ,129.3,138,136.3
BEGIN DESCRIPTION:
Cross Section 20890.6-Interpolated
END DESCRIPTION:
XS GIS Cut Line= 4
      3144331.62      13891622.8      3144491.68     13888972.87
      3144500.58     13888723.88      3144494.52       13888644.
#Sta/Elev= 30
    2243   64.41    2478   63.64    2728   65.23    2853    62.8    2888   64.28
    3023   63.53    3093   64.55    3258   63.38    3303   64.26    3338   63.14
    3398   64.16    3528   62.78    3558   64.24    3593   62.33    3608   63.15
    4013   63.23    4268   62.19  4298.9   63.47    4358   63.57    4388    62.5
  4580.2    62.9  4957.8    62.7  4983.6   62.45  4993.5   55.54  4999.5    55.1
  5009.5   57.15  5018.4   62.55  5151.9   62.14  5211.9    62.8    5227      64
#Mann= 6 , 1 , 0
    2243     .99       0  4298.9      .1       0  4580.2     .14       0
  4957.8      .1       0  4983.6     .04       0  5018.4      .1       0
#XS Ineff= 2 , 0
       0    4853   63.32  5047.8       0   62.63
Permanent Ineff=
       F       F
Bank Sta=4983.6,5018.4
XS Rating Curve= 0
Exp/Cntr=.5,.3

Type RM Length L Ch R = 1 ,20752.6 ,46,46,46
BEGIN DESCRIPTION:
Upstream Section of Bridge/Culvert/Weir
END DESCRIPTION:
XS GIS Cut Line= 6
      3144547.29     13890891.37       3144570.8     13890311.84
      3144621.17     13889181.33      3144633.29     13888876.81
      3144635.84     13888785.15      3144646.39      13888427.6
#Sta/Elev= 30
  2983.6   64.43    3052   64.41    3087   63.45  3377.4   63.67    3522   62.98
    3562   64.34    3582   62.52    3747   62.39    3777    63.1    3837   62.41
    3867   63.09    4092   62.54    4197   63.45    4272   62.27    4287   63.23
    4350   63.38    4372    62.7  4604.4   62.81    4722    63.2    4759   61.91
  4961.8   62.56  4979.9   62.58  4983.8   61.54  4995.3   55.58  4999.6   55.08
  5007.1   55.77  5013.9   58.02  5019.5   62.71  5449.3   63.36  5449.4      64
#Mann= 7 , 1 , 0
  2983.6     .14       0  3377.4     .99       0    4350      .1       0
  4604.4     .14       0  4961.8      .1       0  4983.8     .04       0
  5019.5      .1       0
#XS Ineff= 2 , 0
       0    4976    62.6    5026       0    63.1
Permanent Ineff=
       F       F
Bank Sta=4983.8,5019.5
XS Rating Curve= 0
Exp/Cntr=.5,.3

Type RM Length L Ch R = 3 ,20729.6 ,,,
BEGIN DESCRIPTION:
SUBURBAN ROAD
Structure ID: P26-5,,,,
END DESCRIPTION:
Bridge Culvert--1,0,-1,-1, 0
Deck Dist Width WeirC Skew NumUp NumDn MinLoCord MaxHiCord MaxSubmerge Is_Ogee
10,26,2.6,0, 60, 60, , , .95, 0, 1,1,,
  2983.6    3027    3052    3087    3222    3232    3267    3282    3297    3312
  3343.6    3372    3387    3522    3537    3552    3562    3582  3628.7    3747
    3777    3822    3837    3867    4092    4107    4187    4197    4257    4272
    4287    4347    4372    4392    4407    4422    4532    4652    4662    4722
    4737    4756  4804.1  4859.8  4918.3  4979.9  4983.8 4985.99  4986.1 4986.31
 5015.99  5016.1  5019.5  5020.3 5020.41  5052.3  5143.2  5253.6  5449.3  5449.4
   64.43   64.35   64.42   64.23   63.98   63.96   64.09   64.09   63.99   63.88
   63.64   63.67    63.9    63.8   63.82   64.37   64.35   63.86   63.39   63.37
   63.34    63.3   63.29   63.26   63.05   63.04   63.17   63.46   63.09   62.89
   63.24   63.48    62.8   62.78   63.26   62.75   62.65   63.08   62.81   63.21
   62.68   62.45   62.57   62.86   63.07    63.5   63.53   63.55   64.55   64.55
   64.51   64.51   64.49   64.49   63.49   63.35   63.11   62.85   63.36      64
   64.43   64.16   64.41   63.45   63.85   63.55   63.93   63.54   63.82   63.42
   63.49   63.55   63.89   62.98   63.48   64.36   64.34   62.52   62.48   62.39
    63.1   62.93   62.41   63.09   62.54    62.9   63.16   63.45   63.08   62.27
   63.23   63.47    62.7   62.75   63.25   62.75   62.42   63.07    62.8    63.2
   62.67   62.02   62.32   62.02   62.52   62.58   61.54   60.43   60.38   60.27
   60.21   59.86   62.71   62.72   62.72    63.1   62.51   62.84   63.36      64
  2983.6    3027    3052    3087    3222    3232    3267    3282    3297    3312
  3343.6    3372    3387    3522    3537    3552    3562    3582  3628.7    3747
    3777    3822    3837    3867    4092    4107    4187    4197    4257    4272
    4287    4347    4372    4392    4407    4422    4532    4652    4662    4722
    4737    4756  4804.1  4859.8  4918.3  4979.9  4983.8 4985.99  4986.1 4986.31
 5015.99  5016.1  5019.5  5020.3 5020.41  5052.3  5143.2  5253.6  5449.3  5449.4
   64.43   64.35   64.42   64.23   63.98   63.96   64.09   64.09   63.99   63.88
   63.64   63.67    63.9    63.8   63.82   64.37   64.35   63.86   63.39   63.37
   63.34    63.3   63.29   63.26   63.05   63.04   63.17   63.46   63.09   62.89
   63.24   63.48    62.8   62.78   63.26   62.75   62.65   63.08   62.81   63.21
   62.68   62.45   62.57   62.86   63.07    63.5   63.53   63.55   64.55   64.55
   64.51   64.51   64.49   64.49   63.49   63.35   63.11   62.85   63.36      64
   64.22   63.95    64.2   63.24   63.64   63.34   63.72   63.33   63.61   63.21
   63.28   63.34   63.68   62.77   63.27   64.15   64.13   62.31   62.27   62.18
   62.89   62.72    62.2   62.88   62.33   62.69   62.95   63.24   62.87   62.06
   63.02   63.26   62.49   62.54   63.04   62.54   62.21   62.86   62.59   62.99
   62.46   61.81   62.11   61.81   62.31   62.37   61.33   60.22   60.17   60.06
      60   59.65    62.5   62.51   62.51   62.89    62.3   62.63   63.15   63.79
Abutment Skew #Up #Dn= , 2 , 2
    4986    4988
   60.33   59.42
    4986    4988
   60.12   59.21
Abutment Skew #Up #Dn= , 2 , 2
  5013.9 5016.19
   58.02   60.21
  5013.9 5016.19
   57.81      60
BR Coef= 1 , 1 , 0 ,1.25, 0 ,,,.8,0,2,0,
WSPro=,,,, 1 ,,,, 0 ,,,, 0 ,,,,-1 ,-1 ,-1 , 0 , 0 , 0 , 0 , 0
BR U #Sta/Elev= 107
  2983.6   64.43    3027   64.16    3052   64.41    3087   63.45    3222   63.85
    3232   63.55  3263.6   63.89    3267   63.93  3268.6   63.89    3282   63.54
    3287   63.58    3292   63.82  3293.6   63.82    3297   63.82    3312   63.42
  3343.6   63.49    3372   63.55  3377.4   63.67    3387   63.89    3522   62.98
    3537   63.48    3547   64.16    3552   64.36    3562   64.34    3567   64.05
    3577   62.83    3582   62.52  3593.7   62.51  3628.7   62.48  3633.7   62.48
    3747   62.39    3777    63.1    3822   62.93    3837   62.41    3867   63.09
    3897   62.85    3912   63.05    4092   62.54    4107    62.9    4187   63.16
    4197   63.45    4257   63.08    4272   62.27    4287   63.23    4332   63.38
    4337   63.25    4347   63.47    4350   63.38    4372    62.7    4392   62.75
    4407   63.25    4422   62.75    4527   62.59    4532   62.42  4604.4   62.81
    4652   63.07    4662    62.8    4722    63.2    4737   62.67    4756   62.02
  4758.2   61.94    4759   61.91  4804.1   62.32  4814.4   62.26  4859.8   62.02
  4873.3   62.14  4918.3   62.52  4930.7   62.53  4961.8   62.56  4979.9   62.58
  4983.8   61.54 4985.91   60.47 4985.99   60.43  4986.1   60.38  4986.2   60.33
 4986.31   60.27  4987.9   59.47    4988   59.42  4995.3   55.58  4999.2   55.17
  4999.6   55.08    5000   55.08  5000.5   55.16  5000.7   55.24  5000.9   55.26
  5007.1   55.77  5013.8   57.99  5013.9   58.02 5015.99   59.77  5016.1   59.86
  5016.2   59.95  5019.5   62.71 5020.19   62.72  5020.3   62.72 5020.41   62.72
  5052.3    63.1  5075.9    62.8  5082.9   62.71  5133.5   62.54  5143.2   62.51
  5193.9   62.61  5199.7   62.62  5252.4   62.84  5253.6   62.84  5410.6   63.26
  5449.3   63.36  5449.4      64
BR U #Mann= 7
  2983.6     .14  3377.4     .99    4350      .1  4604.4     .14  4961.8      .1
  4983.8     .04  5019.5      .1
BR U Banks=4983.8,5019.5
BR D #Sta/Elev= 107
  2983.6   64.22    3027   63.95    3052    64.2    3087   63.24    3222   63.64
    3232   63.34  3263.6   63.68    3267   63.72  3268.6   63.68    3282   63.33
    3287   63.37    3292   63.61  3293.6   63.61    3297   63.61    3312   63.21
  3343.6   63.28    3372   63.34  3377.4   63.46    3387   63.68    3522   62.77
    3537   63.27    3547   63.95    3552   64.15    3562   64.13    3567   63.84
    3577   62.62    3582   62.31  3593.7    62.3  3628.7   62.27  3633.7   62.27
    3747   62.18    3777   62.89    3822   62.72    3837    62.2    3867   62.88
    3897   62.64    3912   62.84    4092   62.33    4107   62.69    4187   62.95
    4197   63.24    4257   62.87    4272   62.06    4287   63.02    4332   63.17
    4337   63.04    4347   63.26    4350   63.17    4372   62.49    4392   62.54
    4407   63.04    4422   62.54    4527   62.38    4532   62.21  4604.4    62.6
    4652   62.86    4662   62.59    4722   62.99    4737   62.46    4756   61.81
  4758.2   61.73    4759    61.7  4804.1   62.11  4814.4   62.05  4859.8   61.81
  4873.3   61.93  4918.3   62.31  4930.7   62.32  4961.8   62.35  4979.9   62.37
  4983.8   61.33 4985.91   60.26 4985.99   60.22  4986.1   60.17  4986.2   60.12
 4986.31   60.06  4987.9   59.26    4988   59.21  4995.3   55.37  4999.2   54.96
  4999.6   54.87    5000   54.87  5000.5   54.95  5000.7   55.03  5000.9   55.05
  5007.1   55.56  5013.8   57.78  5013.9   57.81 5015.99   59.56  5016.1   59.65
  5016.2   59.74  5019.5    62.5 5020.19   62.51  5020.3   62.51 5020.41   62.51
  5052.3   62.89  5075.9   62.59  5082.9    62.5  5133.5   62.33  5143.2    62.3
  5193.9    62.4  5199.7   62.41  5252.4   62.63  5253.6   62.63  5410.6   63.05
  5449.3   63.15  5449.4   63.79
BR D #Mann= 7
  2983.6     .14  3377.4     .99    4350      .1  4604.4     .14  4961.8      .1
  4983.8     .04  5019.5      .1
BR D Banks=4983.8,5019.5
BC Design=,, 0 ,, 0 ,,,,,,

Type RM Length L Ch R = 1 ,20706.6 ,355.2,355.2,355.2
BEGIN DESCRIPTION:
Downstream Section of Bridge/Culvert/Weir
END DESCRIPTION:
XS GIS Cut Line= 6
      3144593.24     13890893.42      3144616.76     13890313.88
      3144667.13     13889183.37      3144679.25     13888878.85
       3144681.8     13888787.19      3144692.34     13888429.65
#Sta/Elev= 30
  2983.6   64.19    3052   64.17    3087   63.21  3377.4   63.43    3522   62.74
    3562    64.1    3582   62.28    3747   62.15    3777   62.86    3837   62.17
    3867   62.85    4092    62.3    4197   63.21    4272   62.03    4287   62.99
    4350   63.14    4372   62.46  4604.4   62.57    4722   62.96    4759   61.67
  4961.8   62.32  4979.9   62.34  4983.8    61.3  4995.3   55.34  4999.6   54.84
  5007.1   55.53  5013.9   57.78  5019.5   62.47  5449.3   63.12  5449.4   63.76
#Mann= 7 , 1 , 0
  2983.6     .14       0  3377.4     .99       0    4350      .1       0
  4604.4     .14       0  4961.8      .1       0  4983.8     .04       0
  5019.5      .1       0
#XS Ineff= 2 , 0
       0    4976    62.4    5026       0    63.1
Permanent Ineff=
       F       F
Bank Sta=4983.8,5019.5
XS Rating Curve= 0
Exp/Cntr=.5,.3

Type RM Length L Ch R = 1 ,20351.4 ,368.8,356.9,349.5
BEGIN DESCRIPTION:
Cross Section 20351.4-Interpolated
END DESCRIPTION:
XS GIS Cut Line= 5
      3145015.32     13890187.14      3145016.34     13890146.67
      3145034.12     13888999.55      3145034.12     13888839.48
      3145034.53     13888684.49
#Sta/Elev= 30
  3705.4    63.6  4200.8    63.3  4215.8   62.95  4290.8   63.76  4320.8   62.97
  4395.9   63.33  4455.8   63.62  4470.8   63.07  4530.8   64.33  4575.8   62.97
  4604.5    63.4  4680.8   64.55  4770.8   63.06  4785.8   63.41  4933.1   63.13
  4948.1   64.03  4963.1    63.9  4968.1      63  4993.1   56.73  4993.7   54.72
  5000.7   53.89  5006.3   55.08  5021.5   63.23  5028.1   64.19  5078.2   64.21
  5113.2   63.83  5128.2   63.14  5168.2   62.94  5183.2   63.68  5208.2   63.81
#Mann= 5 , 1 , 0
  3705.4     .14       0  4395.9      .1       0  4604.5     .14       0
  4963.1     .04       0  5021.5     .14       0
Bank Sta=4963.1,5021.5
XS Rating Curve= 0
Exp/Cntr=.3,.1

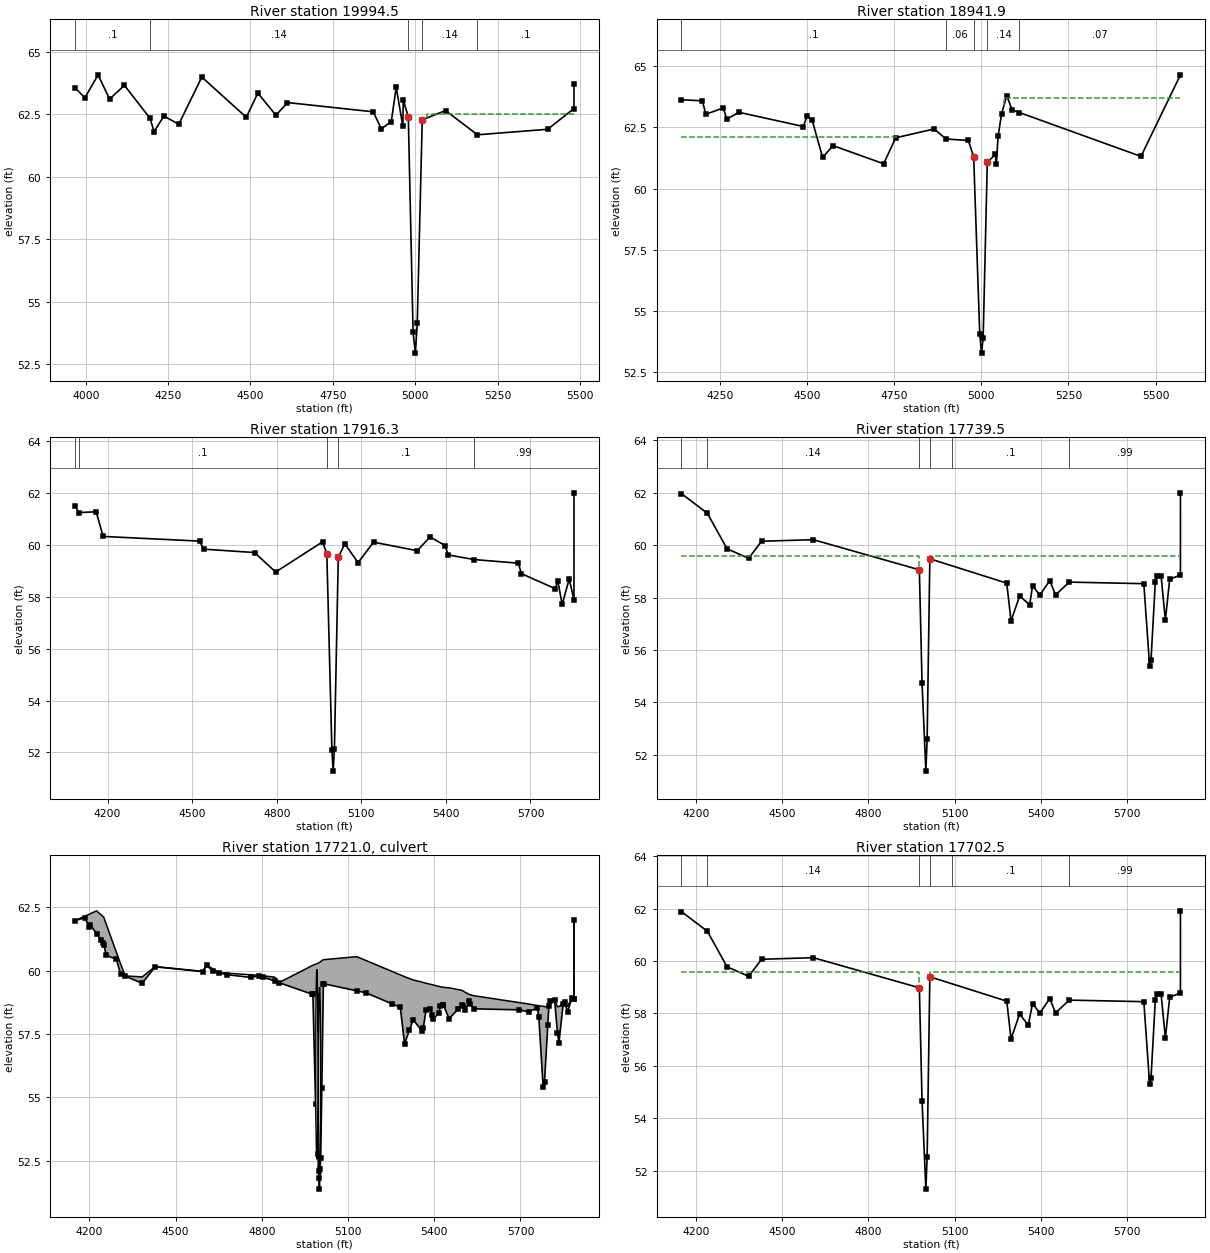
Type RM Length L Ch R = 1 ,19994.5 ,1072.1,1052.6,1049.6
BEGIN DESCRIPTION:
Cross Section 19994.5
END DESCRIPTION:
XS GIS Cut Line= 3
      3145398.44     13889933.56      3145390.23     13888808.85
      3145306.76     13888428.12
#Sta/Elev= 30
  3967.5   63.56  3997.5   63.16  4037.5   64.08  4072.5   63.11  4117.5   63.66
  4195.2   62.34  4207.5   61.81  4237.5   62.43  4282.5    62.1  4352.5   63.99
  4487.5   62.38  4522.5   63.35  4577.5   62.46  4612.5   62.97  4872.5    62.6
  4897.5   61.92  4927.5   62.21  4942.5   63.58  4962.5   62.03    4964   63.07
  4979.2   62.39  4993.7   53.77  5000.7   52.94  5006.3   54.13  5021.5   62.28
  5092.2   62.65  5189.1   61.68  5402.2    61.9    5482   62.73  5482.1    63.7
#Mann= 5 , 1 , 0
  3967.5      .1       0  4195.2     .14       0  4979.2     .04       0
  5021.5     .14       0  5189.1      .1       0
#XS Ineff= 2 , 0
       0  4937.5    63.1  5035.5       0   62.53
Permanent Ineff=
       F       F
Bank Sta=4979.2,5021.5
XS Rating Curve= 0
Exp/Cntr=.3,.1

Type RM Length L Ch R = 1 ,18941.9 ,1099.6,1025.6,1009.6
BEGIN DESCRIPTION:
Cross Section 18941.9
END DESCRIPTION:
XS GIS Cut Line= 5
       3146320.2     13889823.39       3146320.2     13889823.36
      3146440.98     13888965.86      3146440.98     13888928.27
      3146384.12     13888402.96
#Sta/Elev= 30
  4139.4   63.63  4199.4   63.59  4209.4   63.04  4259.4    63.3  4269.4   62.84
  4304.4   63.12  4489.4   62.54  4499.4   62.96  4514.4    62.8  4544.4   61.28
  4574.4   61.76  4719.4   61.02  4754.4   62.08  4864.4   62.44  4898.7   62.03
  4962.6   61.97  4977.9    61.3  4995.3   54.08  5000.5   53.29  5005.1   53.91
    5017   61.08  5040.1    61.4    5043      61    5048   62.15    5058   63.06
    5073    63.8    5088   63.22  5109.3   63.11    5458   61.32  5571.3   64.65
#Mann= 5 , 1 , 0
  4139.4      .1       0  4898.7     .06       0  4977.9     .04       0
    5017     .14       0  5109.3     .07       0
#XS Ineff= 2 , 0
       0  4759.5    62.1  5065.4       0    63.7
Permanent Ineff=
       F       F
Bank Sta=4977.9,5017
XS Rating Curve= 0
Exp/Cntr=.3,.1

Type RM Length L Ch R = 1 ,17916.3 ,124.3,176.8,173.1
BEGIN DESCRIPTION:
Cross Section 17916.3
END DESCRIPTION:
XS GIS Cut Line= 6
      3147454.92     13889916.37      3147487.78     13889788.78
      3147487.78      13889283.7      3147460.23     13889118.41
      3147443.42     13888615.61       3147200.9      13888222.5
#Sta/Elev= 30
  4084.3    61.5  4097.4   61.24  4159.3   61.27  4184.3   60.32    4526   60.14
    4541   59.83  4721.1    59.7  4796.1   58.95  4962.4   60.11  4977.7   59.65
  4995.7   52.08  5000.1   51.28  5004.6   52.13  5018.3   59.51  5041.4   60.04
  5088.5   59.31  5143.5    60.1  5298.5   59.77  5343.5    60.3  5397.5   59.97
  5407.5   59.61    5500   59.43  5657.5   59.29  5667.5   58.89  5787.5   58.31
  5797.5   58.59  5812.5    57.7  5837.5   58.68  5854.4   57.87  5854.5      62
#Mann= 5 , 1 , 0
  4084.3     .14       0  4097.4      .1       0  4977.7     .04       0
  5018.3      .1       0    5500     .99       0
#XS Ineff= 2 , 0
       0                  5343.5       0    59.8
Permanent Ineff=
       F       F
Bank Sta=4977.7,5018.3
XS Rating Curve= 0
Exp/Cntr=.5,.3

Type RM Length L Ch R = 1 ,17739.5 ,37,37,37
BEGIN DESCRIPTION:
Upstream Section of Bridge/Culvert/Weir
END DESCRIPTION:
XS GIS Cut Line= 6
      3147627.63     13889863.73        3147637.      13889100.8
      3147654.51     13888745.24       3147655.7     13888487.88
      3147672.45     13888379.51      3147673.73     13888128.92
#Sta/Elev= 30
  4149.7   61.97  4239.7   61.22  4308.6   59.86  4383.6    59.5  4428.6   60.15
  4608.6   60.21  4977.6   59.06    4987   54.72  5000.3   51.37  5004.7    52.6
  5014.1   59.48  5281.8   58.55  5296.6   57.11  5326.6   58.06  5361.6   57.72
  5371.6   58.46  5396.6   58.09  5431.6   58.65  5451.6    58.1  5499.2   58.59
  5758.8   58.53  5778.8    55.4  5783.8   55.62  5798.8    58.6  5803.8   58.81
  5818.8   58.83  5833.8   57.14  5848.8    58.7  5886.2   58.86  5886.3      62
#Mann= 6 , 1 , 0
  4149.7      .1       0  4239.7     .14       0  4977.6     .04       0
  5014.1     .14       0    5090      .1       0  5499.2     .99       0
#XS Ineff= 2 , 0
       0    4977    59.6    5015       0    59.6
Permanent Ineff=
       F       F
Bank Sta=4977.6,5014.1
XS Rating Curve= 0
Exp/Cntr=.5,.3

Type RM Length L Ch R = 2 ,17721.0 ,,,
BEGIN DESCRIPTION:
ACCESS ROAD
Structure ID: P26-4
END DESCRIPTION:
Bridge Culvert--1,0,-1,-1, 0
Deck Dist Width WeirC Skew NumUp NumDn MinLoCord MaxHiCord MaxSubmerge Is_Ogee
10,17,3,0, 60, 60, , , .95, 0, 1,1,,
  4149.7  4183.6  4198.6  4203.6  4224.7  4249.7  4258.6  4293.6  4308.6  4324.7
  4383.6  4428.6  4593.6  4608.6  4649.7  4790.7  4844.7  4860.7  4977.6    4987
  4995.4  4997.2  5000.3  5002.8  5004.7  5008.7  5014.1  5130.5  5281.8  5296.6
  5326.6  5356.6  5361.6  5371.6  5386.6  5396.6  5421.6  5431.6  5451.6  5496.6
  5506.6  5521.6  5536.6  5728.8  5758.8  5763.8  5778.8  5783.8  5795.1  5798.8
  5803.8  5818.8  5828.8  5833.8  5848.8  5853.8  5863.8  5878.8  5886.2  5886.3
   61.97   62.15   62.22   62.25   62.36   62.11   61.83   60.73   60.26   59.79
   59.75   60.16   59.97   60.22   59.92   59.81   59.74   59.53   60.21   60.25
   60.29    60.3   60.32   60.34   60.36   60.39   60.43   60.55   59.83   59.76
   59.63   59.55   59.53    59.5   59.46   59.43   59.36   59.34   59.32   59.22
   59.15   59.06   59.01   58.68   58.62   58.61   58.59   58.58   58.56   58.61
   58.82   58.84   58.57   58.58   58.71   58.75   58.59   58.91   58.86      62
   61.97   62.09   61.73    61.8   61.46   61.03    60.6   60.45   59.86   59.78
    59.5   60.15   59.96   60.21   59.91    59.8   59.59   59.52   59.06   54.72
   52.76   52.09   51.37   52.18    52.6   55.38   59.48    59.2   58.55   57.11
   58.06   57.63   57.72   58.46   58.49   58.09    58.6   58.65    58.1   58.64
   58.44   58.78   58.49   58.37   58.53   58.18    55.4   55.62   57.86    58.6
   58.81   58.83   57.55   57.14    58.7   58.74   58.37    58.9   58.86      62
  4149.7  4183.6  4198.6  4203.6  4224.7  4249.7  4258.6  4293.6  4308.6  4324.7
  4383.6  4428.6  4593.6  4608.6  4649.7  4790.7  4844.7  4860.7  4977.6    4987
  4995.4  4997.2  5000.3  5002.8  5004.7  5008.7  5014.1  5130.5  5281.8  5296.6
  5326.6  5356.6  5361.6  5371.6  5386.6  5396.6  5421.6  5431.6  5451.6  5496.6
  5506.6  5521.6  5536.6  5728.8  5758.8  5763.8  5778.8  5783.8  5795.1  5798.8
  5803.8  5818.8  5828.8  5833.8  5848.8  5853.8  5863.8  5878.8  5886.2  5886.3
   61.97   62.15   62.22   62.25   62.36   62.11   61.83   60.73   60.26   59.79
   59.75   60.16   59.97   60.22   59.92   59.81   59.74   59.53   60.21   60.25
   60.29    60.3   60.32   60.34   60.36   60.39   60.43   60.55   59.83   59.76
   59.63   59.55   59.53    59.5   59.46   59.43   59.36   59.34   59.32   59.22
   59.15   59.06   59.01   58.68   58.62   58.61   58.59   58.58   58.56   58.61
   58.82   58.84   58.57   58.58   58.71   58.75   58.59   58.91   58.86      62
    61.9   62.02   61.66   61.73   61.39   60.96   60.53   60.38   59.79   59.71
   59.43   60.08   59.89   60.14   59.84   59.73   59.52   59.45   58.99   54.65
   52.69   52.02    51.3   52.11   52.53   55.31   59.41   59.13   58.48   57.04
   57.99   57.56   57.65   58.39   58.42   58.02   58.53   58.58   58.03   58.57
   58.37   58.71   58.42    58.3   58.46   58.11   55.33   55.55   57.79   58.53
   58.74   58.76   57.48   57.07   58.63   58.67    58.3   58.83   58.79   61.93
BR Coef= 1 , 0 , 0 ,1.25, 0 ,,,.8,-1,2,0,
WSPro=,,,, 1 ,,,, 0 ,,,, 0 ,,,,-1 ,-1 ,-1 , 0 , 0 , 0 , 0 , 0
Culvert=1,7.5,,17,.024,.5,1,1,3,52.55,4991.4,52.2,4991.4,Culvert #1  , 0 ,10
Culvert Bottom n=.024
Culvert=1,1.5,,17,.024,.5,1,1,3,57.59,4995.9,57.55,4995.9,Culvert #2  , 0 ,10
Culvert Bottom n=.024
Culvert=1,7.5,,17,.024,.5,1,1,3,51.85,5001,51.51,5001,Culvert #3  , 0 ,10
Culvert Bottom n=.024
BR U #Sta/Elev= 80
  4149.7   61.97  4183.6   62.09  4198.6   61.73  4203.6    61.8  4224.7   61.46
  4239.7   61.22  4248.6   61.08  4249.7   61.03  4258.6    60.6  4293.6   60.45
  4308.6   59.86  4324.7   59.78  4383.6    59.5  4428.6   60.15  4593.6   59.96
  4608.6   60.21  4628.6   59.97  4649.7   59.91  4678.2   59.84  4761.5   59.73
  4790.7    59.8  4804.7   59.74  4844.7   59.59  4860.7   59.52  4974.4   59.07
  4977.6   59.06    4987   54.72  4995.4   52.76  4997.2   52.09  4998.5   51.79
  5000.3   51.37  5002.8   52.18  5004.7    52.6  5008.7   55.38  5014.1   59.48
  5015.8   59.48  5130.5    59.2  5162.9   59.12  5252.5   58.69  5281.8   58.55
  5296.6   57.11  5313.7   57.65  5326.6   58.06  5356.6   57.63  5361.6   57.72
  5371.6   58.46  5386.6   58.49  5391.6   58.23  5396.6   58.09  5416.6   58.33
  5421.6    58.6  5428.7   58.64  5431.6   58.65  5451.6    58.1  5483.7   58.49
  5496.6   58.64  5499.2   58.59  5506.6   58.44  5521.6   58.78  5526.1   58.69
  5536.6   58.49  5693.8   58.45  5728.8   58.37  5758.8   58.53  5763.8   58.18
  5778.8    55.4  5783.8   55.62  5795.1   57.86  5798.8    58.6  5803.8   58.81
  5818.8   58.83  5828.8   57.55  5833.8   57.14  5848.8    58.7  5853.8   58.74
  5863.8   58.37  5878.8    58.9  5885.2   58.87  5886.2   58.86  5886.3      62
BR U #Mann= 6
  4149.7      .1  4239.7     .14  4977.6     .04  5014.1     .14    5090      .1
  5499.2     .99
BR U Banks=4977.6,5014.1
BR D #Sta/Elev= 80
  4149.7    61.9  4183.6   62.02  4198.6   61.66  4203.6   61.73  4224.7   61.39
  4239.7   61.15  4248.6   61.01  4249.7   60.96  4258.6   60.53  4293.6   60.38
  4308.6   59.79  4324.7   59.71  4383.6   59.43  4428.6   60.08  4593.6   59.89
  4608.6   60.14  4628.6    59.9  4649.7   59.84  4678.2   59.77  4761.5   59.66
  4790.7   59.73  4804.7   59.67  4844.7   59.52  4860.7   59.45  4974.4      59
  4977.6   58.99    4987   54.65  4995.4   52.69  4997.2   52.02  4998.5   51.72
  5000.3    51.3  5002.8   52.11  5004.7   52.53  5008.7   55.31  5014.1   59.41
  5015.8   59.41  5130.5   59.13  5162.9   59.05  5252.5   58.62  5281.8   58.48
  5296.6   57.04  5313.7   57.58  5326.6   57.99  5356.6   57.56  5361.6   57.65
  5371.6   58.39  5386.6   58.42  5391.6   58.16  5396.6   58.02  5416.6   58.26
  5421.6   58.53  5428.7   58.57  5431.6   58.58  5451.6   58.03  5483.7   58.42
  5496.6   58.57  5499.2   58.52  5506.6   58.37  5521.6   58.71  5526.1   58.62
  5536.6   58.42  5693.8   58.38  5728.8    58.3  5758.8   58.46  5763.8   58.11
  5778.8   55.33  5783.8   55.55  5795.1   57.79  5798.8   58.53  5803.8   58.74
  5818.8   58.76  5828.8   57.48  5833.8   57.07  5848.8   58.63  5853.8   58.67
  5863.8    58.3  5878.8   58.83  5885.2    58.8  5886.2   58.79  5886.3   61.93
BR D #Mann= 6
  4149.7      .1  4239.7     .14  4977.6     .04  5014.1     .14    5090      .1
  5499.2     .99
BR D Banks=4977.6,5014.1
BC Design=,, 0 ,, 0 ,,,,,,

Type RM Length L Ch R = 1 ,17702.5 ,183.3,183.3,183.3
BEGIN DESCRIPTION:
Downstream Section of Bridge/Culvert/Weir
END DESCRIPTION:
XS GIS Cut Line= 6
      3147664.58     13889865.57      3147673.96     13889102.64
      3147691.47     13888747.08      3147692.66     13888489.72
      3147709.41     13888381.35      3147710.68     13888130.75
#Sta/Elev= 30
  4149.7   61.89  4239.7   61.14  4308.6   59.78  4383.6   59.42  4428.6   60.07
  4608.6   60.13  4977.6   58.98    4987   54.64  5000.3   51.29  5004.7   52.52
  5014.1    59.4  5281.8   58.47  5296.6   57.03  5326.6   57.98  5356.6   57.55
  5371.6   58.38  5396.6   58.01  5431.6   58.57  5451.6   58.02  5499.2   58.51
  5758.8   58.45  5778.8   55.32  5783.8   55.54  5798.8   58.52  5803.8   58.73
  5818.8   58.75  5833.8   57.06  5848.8   58.62  5886.2   58.78  5886.3   61.92
#Mann= 6 , 1 , 0
  4149.7      .1       0  4239.7     .14       0  4977.6     .04       0
  5014.1     .14       0    5090      .1       0  5499.2     .99       0
#XS Ineff= 2 , 0
       0    4977    59.6    5015       0    59.6
Permanent Ineff=
       F       F
Bank Sta=4977.6,5014.1
XS Rating Curve= 0
Exp/Cntr=.5,.3