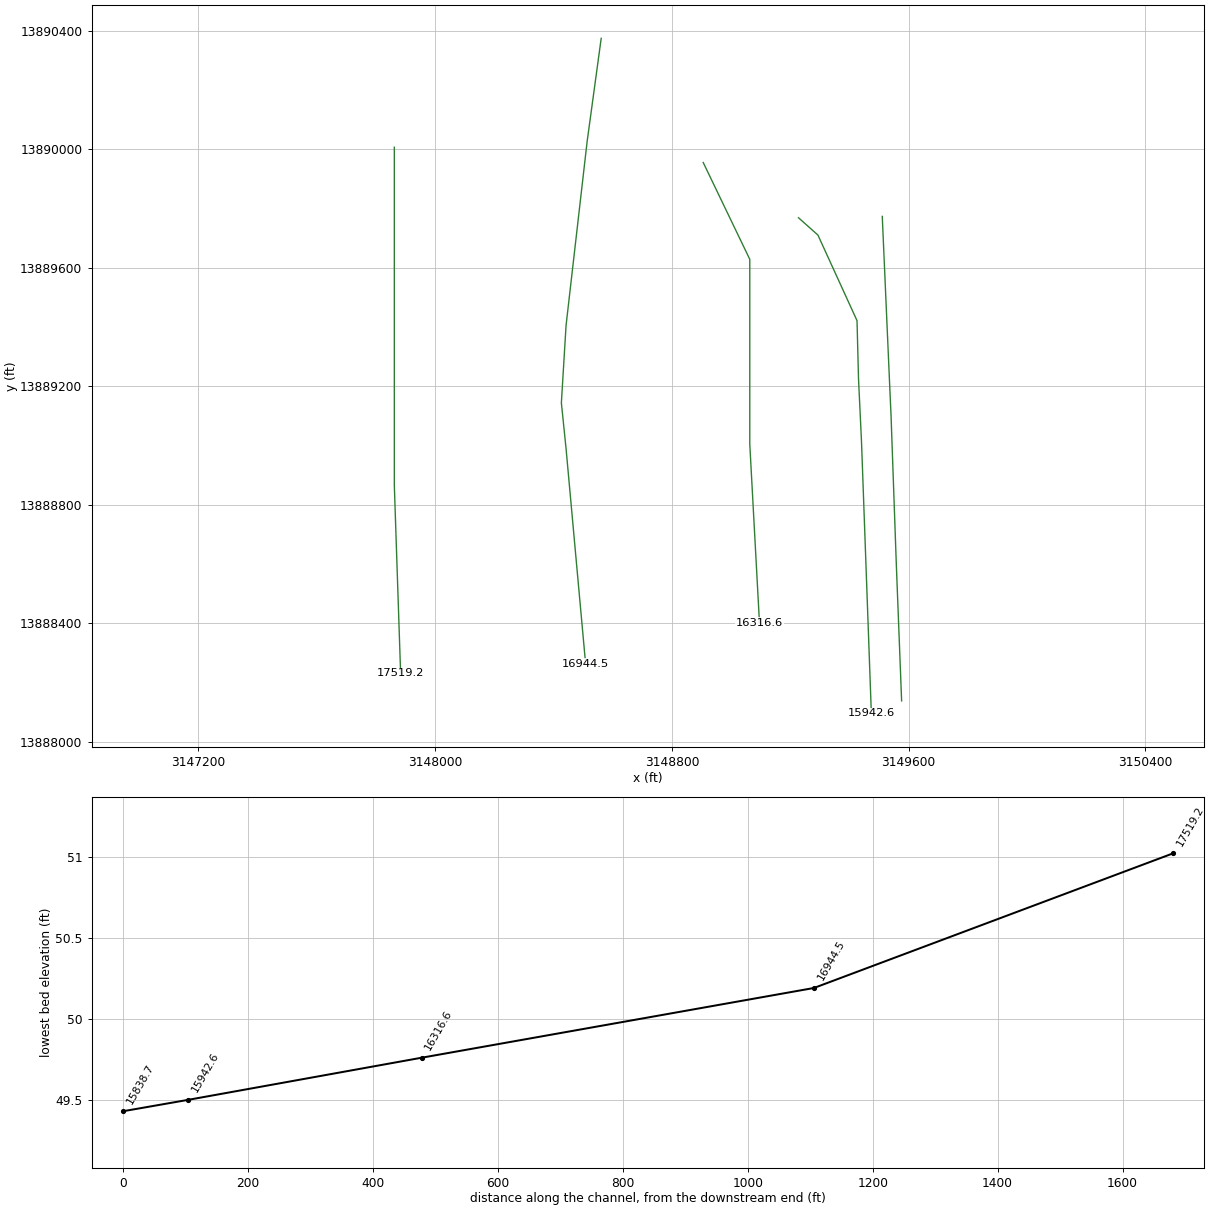
HEC-RAS study P126-00-00.PRJ: P126-00-00

--- P126-00-00.g01 (geometry) --- (continued)

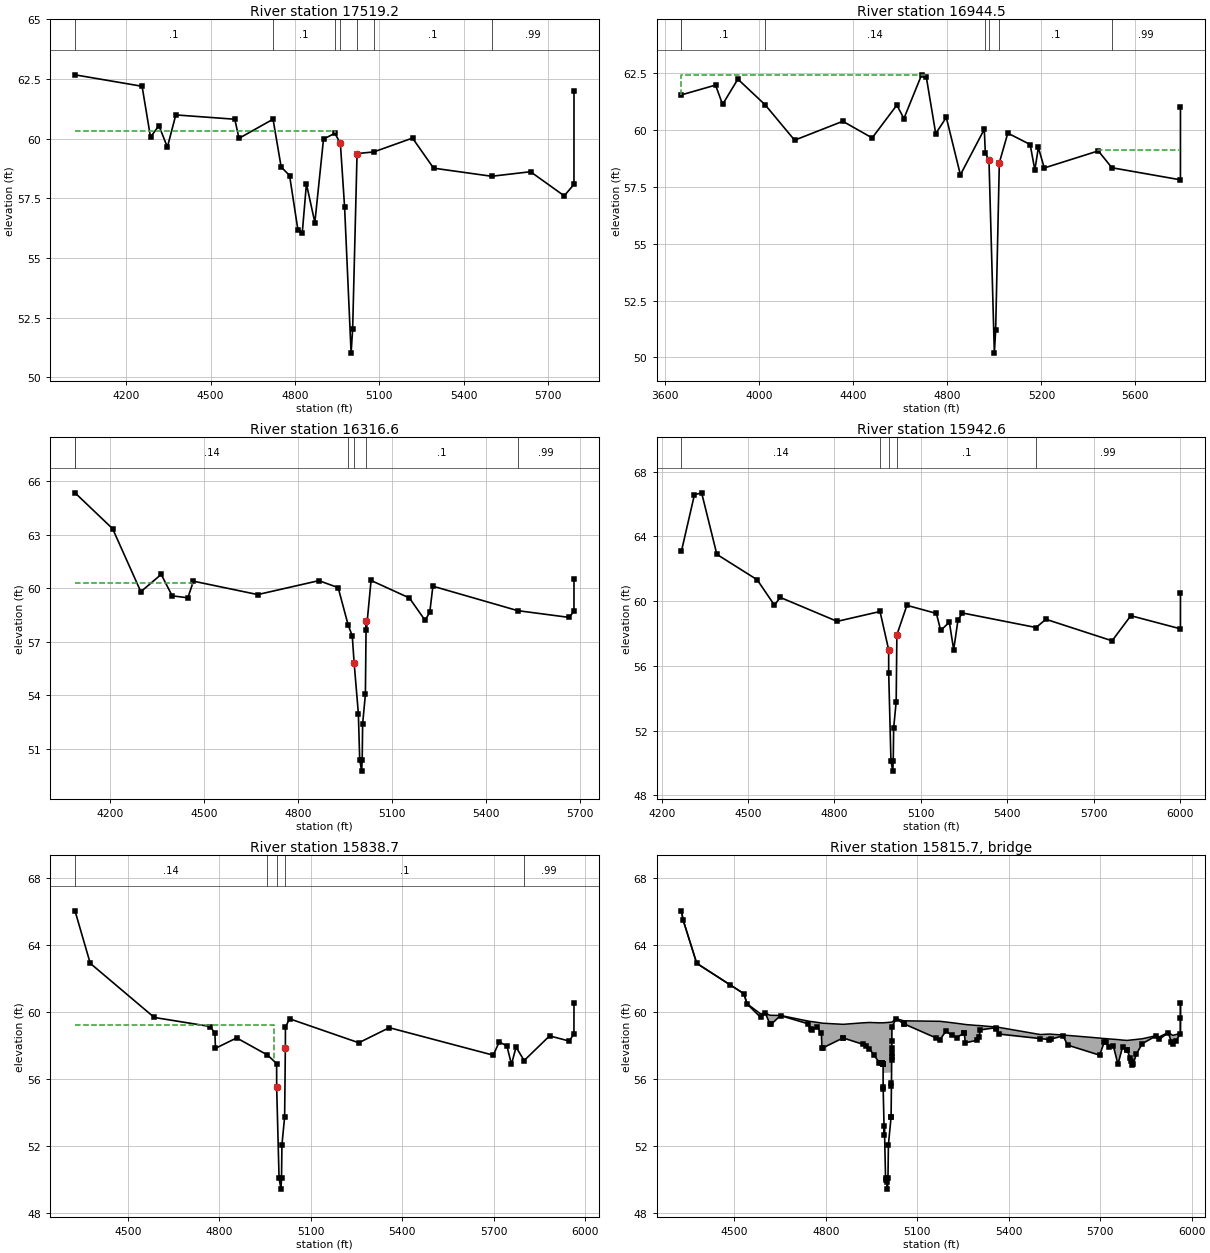
Type RM Length L Ch R = 1 ,17519.2 ,570.1,574.7,628.1
BEGIN DESCRIPTION:
Cross Section 17519.2-Interpolated
END DESCRIPTION:
XS GIS Cut Line= 5
       3147861.9     13890007.56       3147861.9     13889808.75
       3147861.9     13889132.93       3147861.9     13888866.16
      3147883.15     13888231.83
#Sta/Elev= 30
    4017   62.68  4255.8    62.2  4285.8   60.07  4315.8   60.55  4345.8   59.65
  4375.8      61  4585.8   60.82  4600.8   60.02    4722   60.82  4750.8   58.82
  4780.8   58.46  4810.8   56.16  4825.8   56.04  4840.8   58.11  4870.8   56.49
  4901.6   59.99    4942   60.23  4961.6   59.81  4976.6   57.15  4999.8   51.02
  5005.3   52.02    5021   59.38  5080.6   59.45  5218.4   60.03  5293.4   58.77
    5500   58.43  5638.4   58.62  5758.4   57.61  5793.1   58.09  5793.2      62
#Mann= 7 , 1 , 0
    4017      .1       0    4722      .1       0    4942     .14       0
  4961.6     .04       0    5021     .14       0  5080.6      .1       0
    5500     .99       0
#XS Ineff= 2 , 0
       0  4941.6   60.34  5218.4       0    59.8
Permanent Ineff=
       F       F
Bank Sta=4961.6,5021
XS Rating Curve= 0
Exp/Cntr=.3,.1

Type RM Length L Ch R = 1 ,16944.5 ,628.4,627.9,608.7
BEGIN DESCRIPTION:
Cross Section 16944.5
END DESCRIPTION:
XS GIS Cut Line= 6
      3148561.02     13890375.26      3148513.53     13890026.99
      3148442.29     13889405.65      3148426.46     13889144.45
      3148442.29      13888990.1      3148508.36     13888263.63
#Sta/Elev= 30
  3668.4   61.53  3813.4   61.96  3843.4   61.11  3908.4   62.22  4024.8   61.09
  4149.9   59.54  4354.9   60.37  4479.9   59.64  4584.9   61.08  4614.9   60.49
  4690.3   62.41  4710.3   62.31  4750.3   59.83  4795.3   60.54  4855.3   58.02
    4957   60.02  4961.4   58.98  4976.9   58.66  4999.8   50.19  5005.3   51.19
    5021   58.55    5057   59.85  5152.1   59.35  5172.1   58.23  5187.1   59.22
  5212.1   58.32  5442.1   59.07    5500   58.33  5791.6    57.8  5791.7      61
#Mann= 7 , 1 , 0
  3668.4      .2       0  3668.4      .1       0  4024.8     .14       0
  4961.4      .1       0  4976.9     .05       0    5021      .1       0
    5500     .99       0
#XS Ineff= 2 , 0
       0  4705.3    62.4  5438.8       0    59.1
Permanent Ineff=
       F       F
Bank Sta=4976.9,5021
XS Rating Curve= 0
Exp/Cntr=.3,.1

Type RM Length L Ch R = 1 ,16316.6 ,367.3,374,372.8
BEGIN DESCRIPTION:
Cross Section 16316.6-Interpolated
END DESCRIPTION:
XS GIS Cut Line= 5
      3148905.82     13889956.06      3149063.21     13889629.15
      3149063.21     13889192.53      3149063.21      13889005.4
        3149096.      13888401.2
#Sta/Elev= 30
  4087.9   65.35  4207.9   63.34  4297.9   59.81  4362.9   60.78  4397.9   59.58
  4447.9   59.47  4465.7    60.4  4670.7   59.65  4865.7   60.43  4927.3   60.04
  4959.3   57.94  4972.3   57.34  4978.2   55.84  4991.8   52.98    4996   50.41
  5002.3   49.76    5004    50.4  5005.4   52.41  5014.2   54.06  5016.6   58.18
  5017.3   57.67  5032.3   60.44  5154.5   59.46  5204.5   58.21  5219.5   58.65
  5229.5   60.12    5500   58.75  5664.5   58.37  5679.5   58.73  5679.6    60.5
#Mann= 6 , 1 , 0
  4087.9      .2       0  4087.9     .14       0  4959.3      .1       0
  4978.2    .045       0  5016.6      .1       0    5500     .99       0
#XS Ineff= 2 , 0
       0  4460.7   60.31               0
Permanent Ineff=
       F       F
Bank Sta=4978.2,5016.6
XS Rating Curve= 0
Exp/Cntr=.3,.1

Type RM Length L Ch R = 1 ,15942.6 ,101,103.9,101.8
BEGIN DESCRIPTION:
Cross Section 15942.6-Interpolated
END DESCRIPTION:
XS GIS Cut Line= 6
      3149227.91     13889769.47      3149293.58     13889710.94
      3149425.67     13889422.06      3149430.72     13889225.03
      3149440.83     13889012.85      3149474.06     13888096.13
#Sta/Elev= 30
  4268.7   63.09  4313.7   66.57  4338.7   66.69  4391.6   62.89  4531.6   61.32
  4591.6   59.75  4611.6   60.23  4809.3   58.75  4958.1   59.36  4988.1   56.99
  4988.2   55.58    4996   50.15  5002.3    49.5    5004   50.14  5005.4   52.15
  5014.2    53.8  5016.6   57.92  5051.4   59.74  5153.8   59.24  5168.8   58.19
  5198.8    58.7  5213.8      57  5228.8   58.83  5243.8   59.27    5500   58.37
  5533.8   58.88  5763.8   57.55  5828.8    59.1  6001.1   58.29  6001.2    60.5
#Mann= 5 , 1 , 0
  4268.7     .14       0  4958.1      .1       0  4988.1    .045       0
  5016.6      .1       0    5500     .99       0
#XS Ineff= 2 , 0
       0                  5051.4       0    59.5
Permanent Ineff=
       F       F
Bank Sta=4988.1,5016.6
XS Rating Curve= 0
Exp/Cntr=.5,.3

Type RM Length L Ch R = 1 ,15838.7 ,46,46,46
BEGIN DESCRIPTION:
Upstream Section of Bridge/Culvert/Weir
END DESCRIPTION:
XS GIS Cut Line= 5
      3149510.98     13889774.05      3149535.67     13889212.39
      3149540.66      13889101.2      3149558.52     13888597.83
      3149576.38     13888138.37
#Sta/Elev= 30
  4326.5   66.03  4376.5    62.9  4586.5   59.67  4770.4   59.13  4785.4   58.72
  4787.4   57.83  4856.9   58.45  4957.8   57.43    4988   56.92  4988.1   55.51
    4996   50.08  5002.3   49.43    5004   50.07  5005.4   52.08  5014.2   53.73
  5016.6   57.85  5016.9   59.09  5030.4   59.59  5257.5   58.16  5357.5   59.06
  5698.4   57.42  5718.4   58.21  5743.4   57.97  5758.4   56.87  5773.4    57.9
    5800    57.1  5883.4   58.57  5948.4   58.26  5963.3   58.71  5963.5   60.51
#Mann= 5 , 1 , 0
  4326.5     .14       0  4957.8      .1       0  4988.1    .045       0
  5016.6      .1       0    5800     .99       0
#XS Ineff= 2 , 0
       0  4978.3    59.2  5025.6       0    58.6
Permanent Ineff=
       F       F
Bank Sta=4988.1,5016.6
XS Rating Curve= 0
Exp/Cntr=.5,.3

Type RM Length L Ch R = 3 ,15815.7 ,,,
BEGIN DESCRIPTION:
SHERIDAN ROAD
Structure ID: P26-03
END DESCRIPTION:
Bridge Culvert--1,0,-1,-1, 0
Deck Dist Width WeirC Skew NumUp NumDn MinLoCord MaxHiCord MaxSubmerge Is_Ogee
10,26,2.6,0, 60, 60, , , .95, 0, 1,1,,
  4326.5  4331.5  4376.5  4531.5  4541.5  4586.5  4601.5  4616.5  4651.5  4740.4
  4750.4  4755.4  4770.4  4785.4  4787.4  4856.9  4921.5  4943.1  4976.1    4988
  4988.1 5015.29  5015.4  5016.6  5016.9  5030.4  5055.5  5174.4  5194.1  5229.4
  5254.4  5257.5  5297.5  5302.5  5307.5  5357.5  5367.5  5503.7  5533.4  5578.4
  5593.4  5698.4  5713.4  5718.4  5728.4  5743.4  5758.4  5773.4  5788.4  5798.4
  5803.4  5808.4  5818.4  5838.4  5883.4  5893.4  5923.4  5938.4  5963.3  5963.5
   66.02    65.5   62.89   61.08   60.48   59.87   59.93   59.79   59.78   59.45
   59.42   59.41   59.37   59.33   59.32   59.25   59.34   59.36   59.34   59.34
   59.34   59.38   59.38   59.38   59.38   59.59   59.46   59.43   59.39   59.31
   59.25   59.24   59.18   59.18   59.17   59.09   59.07   58.64   58.67   58.61
   58.59   58.43    58.4    58.4   58.38   58.36   58.34   58.31   58.29   58.31
   58.32   58.33   58.35   58.39   58.57    58.5   58.76   58.59   58.71    60.5
   66.02    65.5   62.89   61.07   60.47   59.66   59.92   59.28   59.77   59.29
   58.95   58.92   59.12   58.71   57.82   58.44   58.06   57.79   56.95   56.91
   56.34   56.38   55.78   57.84   59.08   59.58   59.29   58.33   58.84   58.46
   58.74   58.15    58.3   58.51   58.92   59.05   58.67    58.4   58.34   58.56
   58.01   57.41   58.19    58.2   57.89   57.96   56.86   57.89   57.72   57.23
    56.8   56.87   57.47    58.1   58.56   58.35   58.75   58.09    58.7    60.5
  4326.5  4331.5  4376.5  4531.5  4541.5  4586.5  4601.5  4616.5  4651.5  4740.4
  4750.4  4755.4  4770.4  4785.4  4787.4  4856.9  4921.5  4943.1  4976.1    4988
  4988.1 5015.29  5015.4  5016.6  5016.9  5030.4  5055.5  5174.4  5194.1  5229.4
  5254.4  5257.5  5297.5  5302.5  5307.5  5357.5  5367.5  5503.7  5533.4  5578.4
  5593.4  5698.4  5713.4  5718.4  5728.4  5743.4  5758.4  5773.4  5788.4  5798.4
  5803.4  5808.4  5818.4  5838.4  5883.4  5893.4  5923.4  5938.4  5963.3  5963.5
   66.02    65.5   62.89   61.08   60.48   59.87   59.93   59.79   59.78   59.45
   59.42   59.41   59.37   59.33   59.32   59.25   59.34   59.36   59.34   59.34
   59.34   59.38   59.38   59.38   59.38   59.59   59.46   59.43   59.39   59.31
   59.25   59.24   59.18   59.18   59.17   59.09   59.07   58.64   58.67   58.61
   58.59   58.43    58.4    58.4   58.38   58.36   58.34   58.31   58.29   58.31
   58.32   58.33   58.35   58.39   58.57    58.5   58.76   58.59   58.71    60.5
    65.9   65.38   62.77   60.95   60.35   59.54    59.8   59.16   59.65   59.17
   58.83    58.8      59   58.59    57.7   58.32   57.94   57.67   56.83   56.79
   56.22   56.26   55.66   57.72   58.96   59.46   59.17   58.21   58.72   58.34
   58.62   58.03   58.18   58.39    58.8   58.93   58.55   58.28   58.22   58.44
   57.89   57.29   58.07   58.08   57.77   57.84   56.74   57.77    57.6   57.11
   56.68   56.75   57.35   57.98   58.44   58.23   58.63   57.97   58.58   60.38
Abutment Skew #Up #Dn= , 2 , 2
  4985.6  4988.2
   56.92   55.42
  4985.6  4988.2
    56.8    55.3
Abutment Skew #Up #Dn= , 2 , 2
  5014.2 5015.49
   53.72   56.38
  5014.2 5015.49
    53.6   56.26
BR Coef= 1 , 1 , 0 ,1.25, 0 ,,,.8,0,2,0,
WSPro=,,,, 1 ,,,, 0 ,,,, 0 ,,,,-1 ,-1 ,-1 , 0 , 0 , 0 , 0 , 0
BR U #Sta/Elev= 98
  4326.5   66.02  4331.5    65.5  4376.5   62.89  4485.5   61.61  4531.5   61.07
  4541.5   60.47  4586.5   59.66  4601.5   59.92  4616.5   59.28  4621.5   59.27
  4651.5   59.77  4740.4   59.29  4750.4   58.95  4755.4   58.92  4770.4   59.12
  4785.4   58.71  4787.4   57.82  4790.9   57.85  4856.9   58.44    4858   58.43
  4921.5   58.06  4931.6   57.93  4943.1   57.79  4957.8   57.42  4976.1   56.95
  4985.6   56.92 4985.71   56.92  4985.8   56.92 4986.99   56.91  4987.1   56.91
 4987.21   56.91    4988   56.91  4988.1    55.5  4988.2   55.42  4991.8   52.64
  4992.3   53.21    4996   50.07  4997.8   49.94  5000.2   49.86  5002.3   49.42
    5004   50.06  5005.4   52.07  5014.1    53.7  5014.2   53.72 5015.29   55.59
  5015.4   55.78 5016.19   57.14  5016.3   57.32 5016.41   57.51  5016.6   57.84
  5016.7   58.25  5016.9   59.08  5030.4   59.58  5055.5   59.29  5057.6   59.27
  5161.3   58.44  5174.4   58.33  5194.1   58.84  5213.3    58.6  5229.4   58.46
    5254   58.74  5254.4   58.74  5257.5   58.15  5297.5    58.3  5302.5   58.51
  5307.5   58.92  5357.5   59.05    5360   58.96  5367.5   58.67  5503.7    58.4
  5533.4   58.34  5538.7   58.37  5578.4   58.56  5593.4   58.01  5698.4   57.41
  5713.4   58.19  5718.4    58.2  5728.4   57.89  5743.4   57.96  5758.4   56.86
  5773.4   57.89  5788.4   57.72  5788.7   57.71  5798.4   57.23    5800   57.09
  5803.4    56.8  5808.4   56.87  5818.4   57.47  5838.4    58.1  5883.4   58.56
  5893.4   58.35  5923.4   58.75  5933.4   58.22  5938.4   58.09  5948.4   58.25
  5963.3    58.7  5963.4    59.6  5963.5    60.5
BR U #Mann= 5
  4326.5     .14  4957.8      .1  4988.1    .045  5016.6      .1    5800     .99
BR U Banks=4988.1,5016.6
BR D #Sta/Elev= 98
  4326.5    65.9  4331.5   65.38  4376.5   62.77  4485.5   61.49  4531.5   60.95
  4541.5   60.35  4586.5   59.54  4601.5    59.8  4616.5   59.16  4621.5   59.15
  4651.5   59.65  4740.4   59.17  4750.4   58.83  4755.4    58.8  4770.4      59
  4785.4   58.59  4787.4    57.7  4790.9   57.73  4856.9   58.32    4858   58.31
  4921.5   57.94  4931.6   57.81  4943.1   57.67  4957.8    57.3  4976.1   56.83
  4985.6    56.8 4985.71    56.8  4985.8    56.8 4986.99   56.79  4987.1   56.79
 4987.21   56.79    4988   56.79  4988.1   55.38  4988.2    55.3  4991.8   52.52
  4992.3   53.09    4996   49.95  4997.8   49.82  5000.2   49.74  5002.3    49.3
    5004   49.94  5005.4   51.95  5014.1   53.58  5014.2    53.6 5015.29   55.47
  5015.4   55.66 5016.19   57.02  5016.3    57.2 5016.41   57.39  5016.6   57.72
  5016.7   58.13  5016.9   58.96  5030.4   59.46  5055.5   59.17  5057.6   59.15
  5161.3   58.32  5174.4   58.21  5194.1   58.72  5213.3   58.48  5229.4   58.34
    5254   58.62  5254.4   58.62  5257.5   58.03  5297.5   58.18  5302.5   58.39
  5307.5    58.8  5357.5   58.93    5360   58.84  5367.5   58.55  5503.7   58.28
  5533.4   58.22  5538.7   58.25  5578.4   58.44  5593.4   57.89  5698.4   57.29
  5713.4   58.07  5718.4   58.08  5728.4   57.77  5743.4   57.84  5758.4   56.74
  5773.4   57.77  5788.4    57.6  5788.7   57.59  5798.4   57.11    5800   56.97
  5803.4   56.68  5808.4   56.75  5818.4   57.35  5838.4   57.98  5883.4   58.44
  5893.4   58.23  5923.4   58.63  5933.4    58.1  5938.4   57.97  5948.4   58.13
  5963.3   58.58  5963.4   59.48  5963.5   60.38
BR D #Mann= 5
  4326.5     .14  4957.8      .1  4988.1    .045  5016.6      .1    5800     .99
BR D Banks=4988.1,5016.6
BC Design=,, 0 ,, 0 ,,,,,,