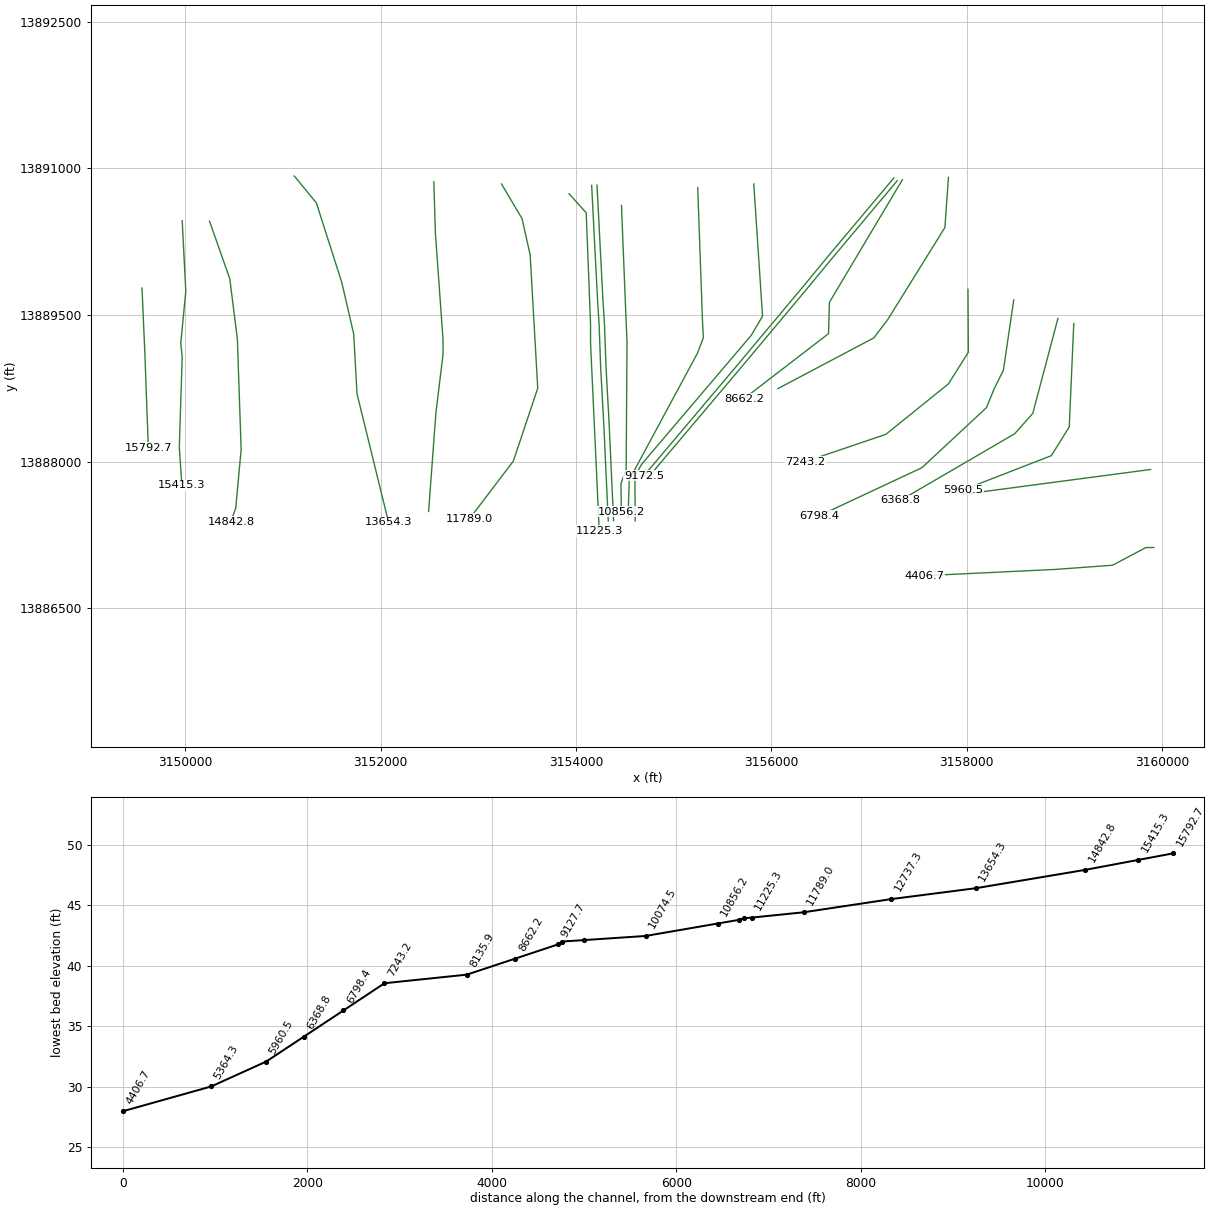
HEC-RAS study P126-00-00.PRJ: P126-00-00

--- P126-00-00.g01 (geometry) --- (continued)

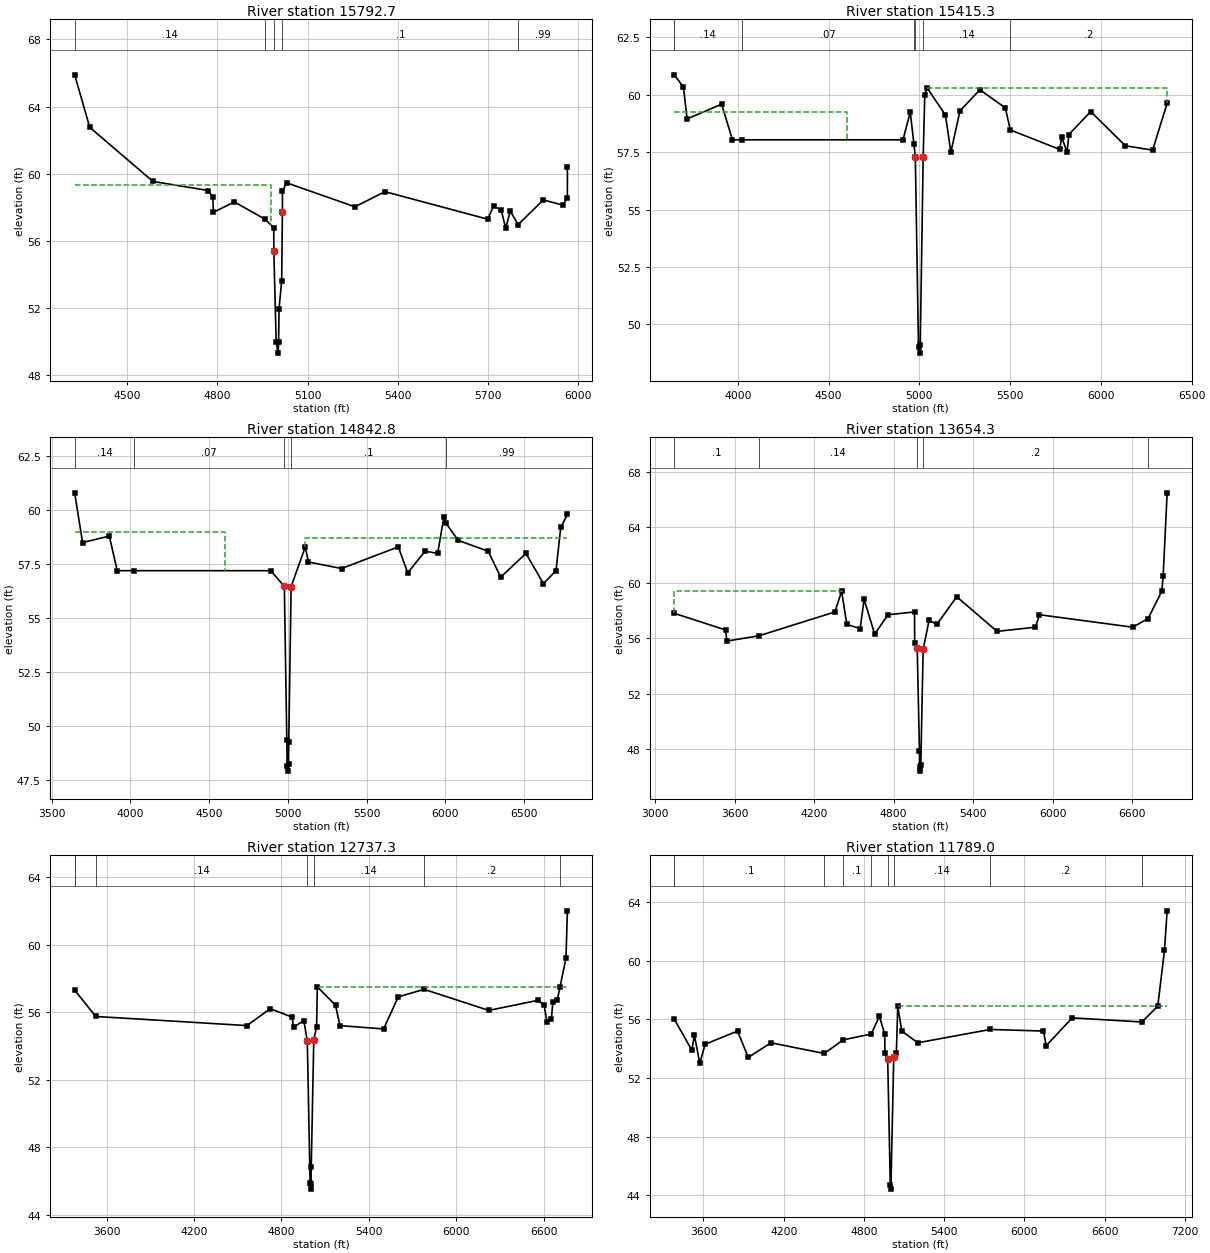
Type RM Length L Ch R = 1 ,15792.7 ,377.4,377.4,377.4
BEGIN DESCRIPTION:
Downstream Section of Bridge/Culvert/Weir
END DESCRIPTION:
XS GIS Cut Line= 5
      3149556.93     13889776.21      3149581.61     13889214.55
       3149586.6     13889103.36      3149604.46     13888599.99
      3149622.33     13888140.53
#Sta/Elev= 30
  4326.5   65.89  4376.5   62.76  4586.5   59.53  4770.4   58.99  4785.4   58.58
  4787.4   57.69  4856.9   58.31  4957.8   57.29    4988   56.78  4988.1   55.37
    4996   49.94  5002.3   49.29    5004   49.93  5005.4   51.94  5014.2   53.59
  5016.6   57.71  5016.9   58.95  5030.4   59.45  5257.5   58.02  5357.5   58.92
  5698.4   57.28  5718.4   58.07  5743.4   57.83  5758.4   56.73  5773.4   57.76
    5800   56.96  5883.4   58.43  5948.4   58.12  5963.3   58.57  5963.5   60.37
#Mann= 5 , 1 , 0
  4326.5     .14       0  4957.8      .1       0  4988.1    .045       0
  5016.6      .1       0    5800     .99       0
#XS Ineff= 2 , 0
       0  4978.3    59.3  5025.6       0    58.4
Permanent Ineff=
       F       F
Bank Sta=4988.1,5016.6
XS Rating Curve= 0
Exp/Cntr=.5,.3

Type RM Length L Ch R = 1 ,15415.3 ,526.7,572.5,612.9
BEGIN DESCRIPTION:
Cross Section 15415.3-Interpolated
END DESCRIPTION:
XS GIS Cut Line= 6
      3149968.36     13890466.13      3150005.29     13889742.31
      3149953.58     13889210.52      3149968.36     13889077.58
      3149938.81     13888146.95      3149965.46     13887757.84
#Sta/Elev= 30
    3651   60.87    3701   60.33    3721   58.95    3911   59.59    3971   58.04
  4021.1   58.04  4910.1   58.04  4950.1   59.25  4970.4   57.85    4978    57.3
  4995.5   49.01  5001.4   48.75  5004.9   49.09  5021.2   57.28  5030.1      60
  5043.8   60.29  5143.8   59.12  5173.8    57.5  5223.8    59.3  5333.8   60.22
  5473.8   59.43    5501   58.47  5773.8   57.62  5783.8   58.17  5813.8    57.5
  5823.8   58.27  5943.8   59.27  6134.9   57.78  6284.9   57.59  6364.9   59.63
#Mann= 7 , 1 , 0
    3651      .2       0    3651     .14       0  4021.1     .07       0
  4970.4      .1       0    4978    .045       0  5021.2     .14       0
    5501      .2       0
#XS Ineff= 2 , 0
       0  4600.1   59.25  5043.8       0   60.29
Permanent Ineff=
       F       F
Bank Sta=4978,5021.2
XS Rating Curve= 0
Exp/Cntr=.3,.1

Type RM Length L Ch R = 1 ,14842.8 ,1167.4,1188.5,1225.1
BEGIN DESCRIPTION:
Cross Section 14842.8
END DESCRIPTION:
XS GIS Cut Line= 6
       3150248.3     13890460.79      3150455.51     13889871.85
      3150533.08     13889256.84      3150571.86     13888126.56
      3150516.46     13887528.17      3150466.57      13887384.1
#Sta/Elev= 30
  3646.9    60.8  3696.9    58.5  3866.9    58.8  3916.9    57.2  4024.2    57.2
  4891.1    57.2    4978   56.48  4993.9   49.35  4995.5   48.19  5001.4   47.93
  5004.9   48.27  5006.1   49.29  5021.2   56.46  5111.1    58.3  5131.1    57.6
  5341.6    57.3  5701.6    58.3  5761.6    57.1  5871.6    58.1  5951.6      58
  5991.6    59.7  6002.8   59.41  6082.1    58.6  6272.1    58.1  6352.1    56.9
  6512.1      58  6623.1    56.6  6703.1    57.2  6733.1    59.2  6775.5    59.8
#Mann= 5 , 1 , 0
  3646.9     .14       0  4024.2     .07       0    4978     .05       0
  5021.2      .1       0  6002.8     .99       0
#XS Ineff= 2 , 0
       0  4600.2      59  5111.1       0    58.7
Permanent Ineff=
       F       F
Bank Sta=4978,5021.2
XS Rating Curve= 0
Exp/Cntr=.3,.1

Type RM Length L Ch R = 1 ,13654.3 ,979.6,917,807.6
BEGIN DESCRIPTION:
Cross Section 13654.3
END DESCRIPTION:
XS GIS Cut Line= 6
      3151115.64     13890922.42      3151342.01     13890647.54
      3151602.42     13889833.07      3151724.31     13889306.71
      3151757.95     13888695.98      3152080.76     13887381.84
#Sta/Elev= 30
  3145.9    57.8    3532    56.6    3542    55.8  3783.6   56.18  4357.1    57.9
  4407.1    59.4  4447.1      57  4547.1    56.7  4577.1    58.8  4657.1    56.3
  4757.1    57.7  4957.4    57.9  4958.5   55.68  4977.8   55.27  4994.6   47.83
  4995.6   46.73  5001.2   46.41  5004.6   46.83  5022.5   55.21  5067.4    57.3
  5125.7      57  5275.7      59  5579.7    56.5  5869.7    56.8  5899.7    57.7
    6603    56.8    6719   57.42    6823    59.4    6833    60.5    6863    66.5
#Mann= 5 , 1 , 0
  3145.9      .1       0  3783.6     .14       0  4977.8    .045       0
  5022.5      .2       0    6719      .2       0
#XS Ineff= 2 , 0
       0  4408.4    59.4  5275.7       0      59
Permanent Ineff=
       F       F
Bank Sta=4977.8,5022.5
XS Rating Curve= 0
Exp/Cntr=.3,.1

Type RM Length L Ch R = 1 ,12737.3 ,944.6,948.3,1056
BEGIN DESCRIPTION:
Cross Section 12737.3
END DESCRIPTION:
XS GIS Cut Line= 6
      3152544.32     13890863.62      3152560.94     13890331.72
      3152638.51      13889251.3      3152638.51     13889096.17
      3152566.49     13888508.86      3152490.74     13887491.66
#Sta/Elev= 30
  3380.9    57.3  3525.7   55.74  4563.1    55.2  4723.4    56.2  4873.4    55.7
  4883.4    55.1  4953.4    55.5  4977.7   54.29  4996.9   45.86  5001.3   45.51
  5003.5    45.8  5004.7   46.82  5022.2   54.36  5041.6   55.13  5046.5    57.5
  5171.6    56.4  5201.6    55.2  5501.6      55  5601.6    56.9  5778.9   57.35
  6223.3    56.1  6563.3    56.7  6603.3    56.4  6623.3    55.4  6653.3    55.6
  6663.3    56.6  6693.3    56.7  6712.1   57.48  6753.3    59.2  6763.3      62
#Mann= 7 , 1 , 0
  3380.9      .2       0  3380.9      .1       0  3525.7     .14       0
  4977.7    .045       0  5022.2     .14       0  5778.9      .2       0
  6712.1      .2       0
#XS Ineff= 2 , 0
       0                  5056.6       0    57.5
Permanent Ineff=
       F       F
Bank Sta=4977.7,5022.2
XS Rating Curve= 0
Exp/Cntr=.3,.1

Type RM Length L Ch R = 1 ,11789.0 ,585.1,563.7,560.2
BEGIN DESCRIPTION:
Cross Section 11789.0
END DESCRIPTION:
XS GIS Cut Line= 6
       3153236.9     13890841.46      3153447.44     13890486.86
      3153530.55     13890115.64      3153608.12     13888752.65
      3153358.39     13888006.82      3152910.17     13887418.01
#Sta/Elev= 30
  3382.6      56  3512.6    53.9  3532.6    54.9  3572.6      53  3612.6    54.3
    3855    55.2    3935    53.4    4105    54.4  4503.4   53.67  4645.3    54.6
  4854.4      55  4915.4    56.2  4955.4      55  4957.2   53.68  4977.6   53.31
    4997   44.73  5001.4   44.42  5022.9   53.41  5042.7   53.73  5052.8    56.9
  5082.8    55.2  5202.8    54.4  5744.4   55.31  6142.7    55.2  6162.7    54.2
  6357.3    56.1  6878.9   55.82  6997.3    56.9  7047.3    60.7  7067.3    63.4
#Mann= 9 , 1 , 0
  3382.6      .2       0  3382.6      .1       0  4503.4     .14       0
  4645.3      .1       0  4854.4     .14       0  4977.6    .045       0
  5022.9     .14       0  5744.4      .2       0  6878.9      .2       0
#XS Ineff= 2 , 0
       0    3855    55.2  5053.1       0    56.9
Permanent Ineff=
       F       F
Bank Sta=4977.6,5022.9
XS Rating Curve= 0
Exp/Cntr=.3,.1

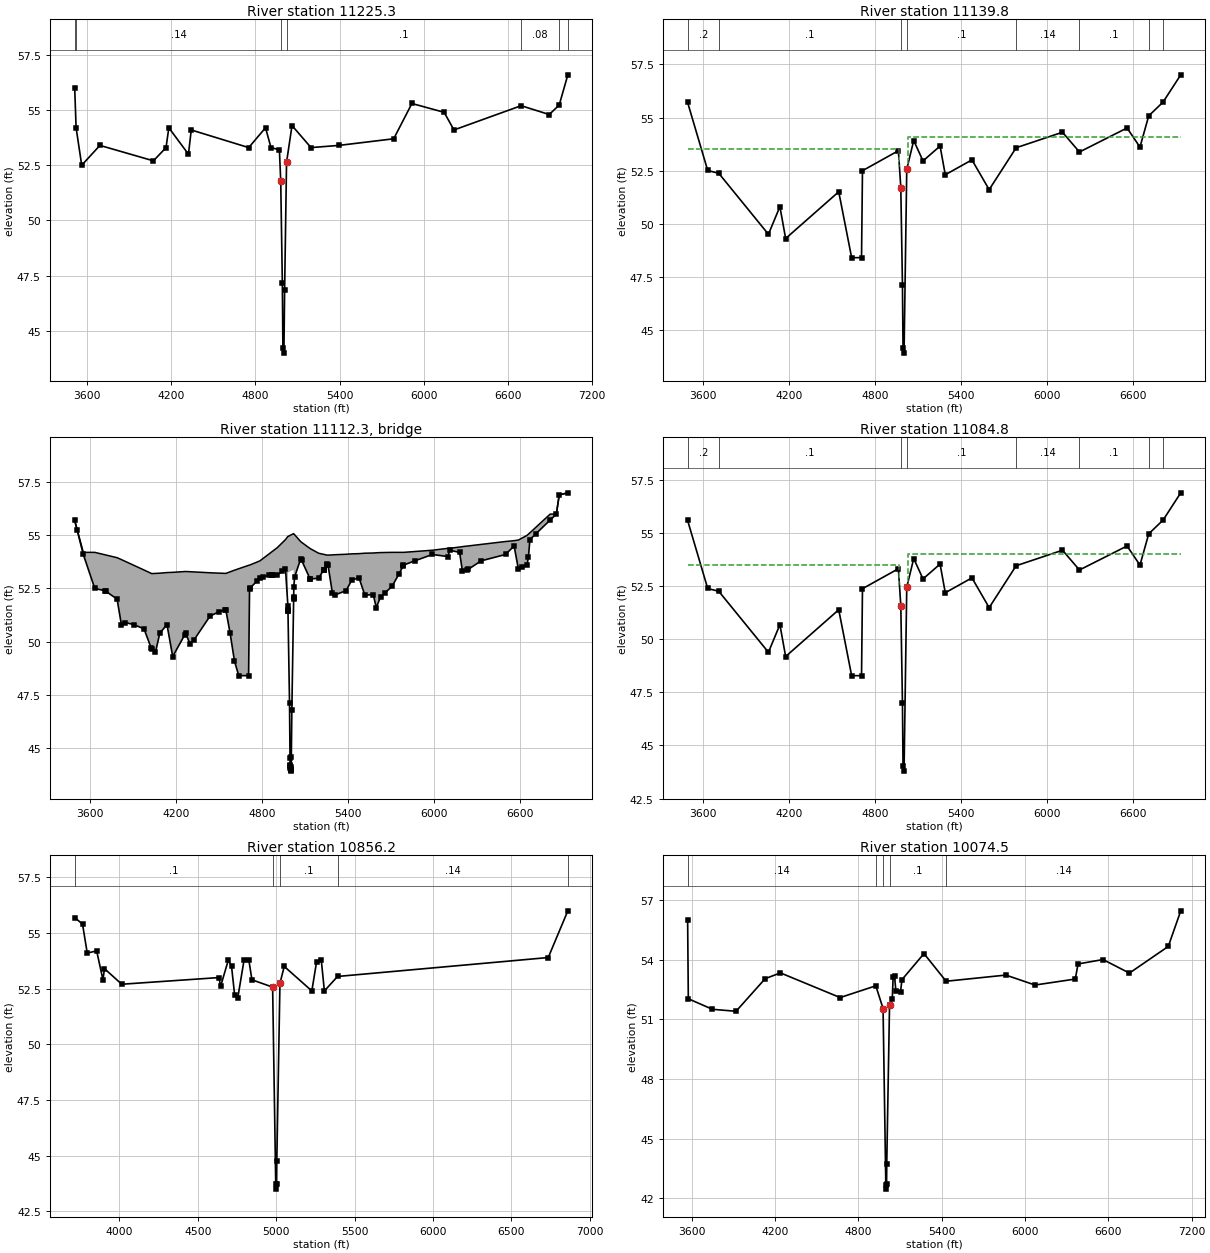
Type RM Length L Ch R = 1 ,11225.3 ,77,85.5,97.4
BEGIN DESCRIPTION:
Cross Section 11225.3-Interpolated
END DESCRIPTION:
XS GIS Cut Line= 5
      3153928.66     13890741.02      3154104.36     13890546.82
      3154148.82      13889408.6      3154148.82     13889212.96
      3154237.75     13887292.21
#Sta/Elev= 30
  3510.1      56  3520.1    54.2  3560.1    52.5  3690.1    53.4  4071.9    52.7
  4161.9    53.3  4181.9    54.2  4321.9      53  4341.9    54.1  4751.9    53.3
  4871.9    54.2    4911    53.3    4971    53.2  4980.5   51.77    4992   47.18
    4996   44.22  5003.2   43.98  5008.3   46.84    5022   52.63    5061    54.3
  5196.7    53.3  5396.7    53.4  5786.7    53.7  5916.7    55.3  6146.7    54.9
  6216.7    54.1  6696.4    55.2  6896.7    54.8    6968   55.23  7029.5    56.6
#Mann= 7 , 1 , 0
  3510.1      .2       0  3520.1     .14       0  4980.5     .04       0
    5022      .1       0  6696.4     .08       0    6968     .14       0
  7029.5      .2       0
Bank Sta=4980.5,5022
XS Rating Curve= 0
Exp/Cntr=.5,.3

Type RM Length L Ch R = 1 ,11139.8 ,55,55,55
BEGIN DESCRIPTION:
Upstream Section of Bridge/Culvert/Weir
END DESCRIPTION:
XS GIS Cut Line= 6
      3154160.15     13890827.07       3154220.6     13889653.22
      3154236.91     13889395.65      3154252.09     13888969.41
      3154283.03     13888409.99      3154330.02     13887394.55
#Sta/Elev= 30
  3494.8   55.71  3634.8   52.51  3711.7   52.38  4057.9   49.51  4137.9   50.81
  4177.9   49.31  4547.9   51.51  4637.9   48.41  4706.8   48.41  4713.4    52.5
  4963.7   53.44  4980.5   51.71    4992   47.12    4996   44.16  5003.1   43.92
    5022   52.57  5070.5   53.92  5135.3   52.96  5254.2   53.66  5290.4   52.31
  5476.3   53.01  5596.3   51.61  5784.3   53.58  6107.3   54.31  6225.6   53.38
  6557.3   54.51  6647.3   53.61  6708.3   55.08  6808.5   55.73  6931.6   57.01
#Mann= 8 , 1 , 0
  3494.8      .2       0  3711.7      .1       0  4980.5     .05       0
    5022      .1       0  5784.3     .14       0  6225.6      .1       0
  6708.3     .14       0  6808.5      .2       0
#XS Ineff= 2 , 0
       0  4971.1    53.5  5030.8       0    54.1
Permanent Ineff=
       F       F
Bank Sta=4980.5,5022
XS Rating Curve= 0
Exp/Cntr=.5,.3

Type RM Length L Ch R = 3 ,11112.3 ,,,
BEGIN DESCRIPTION:
MESA DRIVE
Structure ID: P26-2,,,,
END DESCRIPTION:
Bridge Culvert--1,0,-1,-1, 0
Deck Dist Width WeirC Skew NumUp NumDn MinLoCord MaxHiCord MaxSubmerge Is_Ogee
10,35,2.6,0, 60, 60, , , .95, 0, 1,1,,
  3494.8  3554.8  3634.8  3790.2  3820.2  3977.9  4031.7  4057.9  4087.9  4137.9
  4177.9  4267.9  4297.9  4437.9  4547.9  4607.9  4637.9  4706.8  4713.4  4785.6
  4906.4  4963.7  4980.5 4981.11  4981.2 5020.69  5020.8    5022  5027.5  5070.5
  5135.3  5194.4  5254.2  5260.4  5290.4  5310.4  5386.3  5426.3  5476.3  5516.3
  5576.3  5596.3  5626.3  5706.3  5786.3  5987.3  6097.3  6107.3  6177.3  6197.3
  6497.3  6557.3  6587.3  6647.3  6657.3  6667.3  6808.5  6851.6  6871.6  6931.6
    55.7    54.2    54.2   53.95   53.86   53.37    53.2   53.21   53.22   53.25
   53.26    53.3   53.29   53.24   53.21   53.36   53.43   53.59    53.6    53.8
   54.42    54.8   54.95   54.95   54.95   55.08   55.08   55.07   55.03    54.7
   54.38   54.16   54.07   54.07   54.08   54.09   54.11   54.13   54.14   54.16
   54.17   54.18   54.19    54.2    54.2    54.3   54.39   54.39   54.45   54.47
   54.71   54.75   54.78      55   55.06   55.12      56      56    56.9      57
    55.7    54.1    52.5      52    50.8    50.6   49.67    49.5    50.4    50.8
    49.3    50.4    49.9    51.2    51.5    49.1    48.4    48.4   52.49      53
   53.13   53.43    51.7   51.46   53.25   53.38   52.06   52.56   53.04   53.91
   52.95   52.98   53.65    53.6    52.3    52.2    52.4    52.9      53    52.2
    52.2    51.6    52.1    52.6    53.6    54.1      54    54.3    54.2    53.3
    54.1    54.5    53.4    53.6      54    54.8   55.72      56    56.9      57
  3494.8  3554.8  3634.8  3790.2  3820.2  3977.9  4031.7  4057.9  4087.9  4137.9
  4177.9  4267.9  4297.9  4437.9  4547.9  4607.9  4637.9  4706.8  4713.4  4785.6
  4906.4  4963.7  4980.5 4981.11  4981.2 5020.69  5020.8    5022  5027.5  5070.5
  5135.3  5194.4  5254.2  5260.4  5290.4  5310.4  5386.3  5426.3  5476.3  5516.3
  5576.3  5596.3  5626.3  5706.3  5786.3  5987.3  6097.3  6107.3  6177.3  6197.3
  6497.3  6557.3  6587.3  6647.3  6657.3  6667.3  6808.5  6851.6  6871.6  6931.6
    55.7    54.2    54.2   53.95   53.86   53.37    53.2   53.21   53.22   53.25
   53.26    53.3   53.29   53.24   53.21   53.36   53.43   53.59    53.6    53.8
   54.42    54.8   54.95   54.95   54.95   55.08   55.08   55.07   55.03    54.7
   54.38   54.16   54.07   54.07   54.08   54.09   54.11   54.13   54.14   54.16
   54.17   54.18   54.19    54.2    54.2    54.3   54.39   54.39   54.45   54.47
   54.71   54.75   54.78      55   55.06   55.12      56      56    56.9      57
   55.59   53.99   52.39   51.89   50.69   50.49   49.56   49.39   50.29   50.69
   49.19   50.29   49.79   51.09   51.39   48.99   48.29   48.29   52.38   52.89
   53.02   53.32   51.59   51.35   53.14   53.27   51.95   52.45   52.93    53.8
   52.84   52.87   53.54   53.49   52.19   52.09   52.29   52.79   52.89   52.09
   52.09   51.49   51.99   52.49   53.49   53.99   53.89   54.19   54.09   53.19
   53.99   54.39   53.29   53.49   53.89   54.69   55.61   55.89   56.79   56.89
Abutment Skew #Up #Dn= , 2 , 2
    4981    4996
   53.25   44.15
    4981    4996
   53.14   44.04
Abutment Skew #Up #Dn= , 2 , 2
  5003.2 5020.89
   43.96   53.38
  5003.2 5020.89
   43.85   53.27
BR Coef= 1 , 1 , 0 ,1.25, 0 ,,,.8,0,2,0,
WSPro=,,,, 1 ,,,, 0 ,,,, 0 ,,,,-1 ,-1 ,-1 , 0 , 0 , 0 , 0 , 0
BR U #Sta/Elev= 109
  3494.8    55.7  3511.7   55.25  3554.8    54.1  3634.8    52.5  3704.8    52.4
  3711.7   52.37  3790.2      52  3820.2    50.8  3847.9    50.9  3907.9    50.8
  3977.9    50.6  4027.9    49.7  4031.7   49.67  4057.9    49.5  4087.9    50.4
  4137.9    50.8  4177.9    49.3  4261.7   50.32  4267.9    50.4  4297.9    49.9
  4327.9    50.1  4437.9    51.2  4497.9    51.4  4541.7   51.49  4547.9    51.5
  4577.9    50.4  4607.9    49.1  4637.9    48.4  4706.8    48.4  4713.4   52.49
  4715.9   52.51  4763.4   52.84  4785.6      53  4810.1   53.05  4849.8   53.12
 4871.69   53.12  4871.8   53.12 4871.91   53.12  4872.6   53.12  4906.4   53.13
  4941.7   53.31  4963.7   53.43  4980.5    51.7    4981    51.5 4981.11   51.46
  4981.2   51.42    4992   47.11  4995.4   44.54  4995.9   44.22    4996   44.15
  4997.3   44.05  4999.7   43.95  5000.8   44.03  5001.8    44.1  5003.1   43.91
  5003.2   43.96  5004.5   44.57  5008.2   46.77 5020.69   52.01  5020.8   52.06
  5020.9    52.1    5022   52.56  5027.5   53.04  5070.5   53.91    5076   53.83
  5133.8   52.97  5135.3   52.95  5194.4   52.98 5229.59   53.37  5229.7   53.38
 5229.81   53.38  5251.4   53.62  5254.2   53.65  5260.4    53.6  5290.4    52.3
  5310.4    52.2  5386.3    52.4  5426.3    52.9  5476.3      53  5516.3    52.2
  5576.3    52.2  5596.3    51.6  5626.3    52.1  5654.8   52.28  5706.3    52.6
  5756.3    53.2  5784.3   53.57  5786.3    53.6  5864.8    53.8  5987.3    54.1
  6097.3      54  6107.3    54.3  6177.3    54.2  6197.3    53.3  6225.6   53.37
  6237.3    53.4  6327.3    53.8  6497.3    54.1  6557.3    54.5  6587.3    53.4
  6615.1   53.49  6647.3    53.6  6657.3      54  6667.3    54.8  6708.3   55.07
  6808.5   55.72  6851.6      56  6871.6    56.9  6931.6      57
BR U #Mann= 8
  3494.8      .2  3711.7      .1  4980.5     .05    5022      .1  5784.3     .14
  6225.6      .1  6708.3     .14  6808.5      .2
BR U Banks=4980.5,5022
BR D #Sta/Elev= 109
  3494.8   55.59  3511.7   55.14  3554.8   53.99  3634.8   52.39  3704.8   52.29
  3711.7   52.26  3790.2   51.89  3820.2   50.69  3847.9   50.79  3907.9   50.69
  3977.9   50.49  4027.9   49.59  4031.7   49.56  4057.9   49.39  4087.9   50.29
  4137.9   50.69  4177.9   49.19  4261.7   50.21  4267.9   50.29  4297.9   49.79
  4327.9   49.99  4437.9   51.09  4497.9   51.29  4541.7   51.38  4547.9   51.39
  4577.9   50.29  4607.9   48.99  4637.9   48.29  4706.8   48.29  4713.4   52.38
  4715.9    52.4  4763.4   52.73  4785.6   52.89  4810.1   52.94  4849.8   53.01
 4871.69   53.01  4871.8   53.01 4871.91   53.01  4872.6   53.01  4906.4   53.02
  4941.7    53.2  4963.7   53.32  4980.5   51.59    4981   51.39 4981.11   51.35
  4981.2   51.31    4992      47  4995.4   44.43  4995.9   44.11    4996   44.04
  4997.3   43.94  4999.7   43.84  5000.8   43.92  5001.8   43.99  5003.1    43.8
  5003.2   43.85  5004.5   44.46  5008.2   46.66 5020.69    51.9  5020.8   51.95
  5020.9   51.99    5022   52.45  5027.5   52.93  5070.5    53.8    5076   53.72
  5133.8   52.86  5135.3   52.84  5194.4   52.87 5229.59   53.26  5229.7   53.27
 5229.81   53.27  5251.4   53.51  5254.2   53.54  5260.4   53.49  5290.4   52.19
  5310.4   52.09  5386.3   52.29  5426.3   52.79  5476.3   52.89  5516.3   52.09
  5576.3   52.09  5596.3   51.49  5626.3   51.99  5654.8   52.17  5706.3   52.49
  5756.3   53.09  5784.3   53.46  5786.3   53.49  5864.8   53.69  5987.3   53.99
  6097.3   53.89  6107.3   54.19  6177.3   54.09  6197.3   53.19  6225.6   53.26
  6237.3   53.29  6327.3   53.69  6497.3   53.99  6557.3   54.39  6587.3   53.29
  6615.1   53.38  6647.3   53.49  6657.3   53.89  6667.3   54.69  6708.3   54.96
  6808.5   55.61  6851.6   55.89  6871.6   56.79  6931.6   56.89
BR D #Mann= 8
  3494.8      .2  3711.7      .1  4980.5     .05    5022      .1  5784.3     .14
  6225.6      .1  6708.3     .14  6808.5      .2
BR D Banks=4980.5,5022
BC Design=,, 0 ,, 0 ,,,,,,

Type RM Length L Ch R = 1 ,11084.8 ,228.6,228.6,228.6
BEGIN DESCRIPTION:
Downstream Section of Bridge/Culvert/Weir
END DESCRIPTION:
XS GIS Cut Line= 6
      3154215.08     13890829.89      3154275.52     13889656.04
      3154291.83     13889398.47      3154307.01     13888972.23
      3154337.95     13888412.81      3154384.95     13887397.37
#Sta/Elev= 30
  3494.8   55.58  3634.8   52.38  3711.7   52.25  4057.9   49.38  4137.9   50.68
  4177.9   49.18  4547.9   51.38  4637.9   48.28  4706.8   48.28  4713.4   52.37
  4963.7   53.31  4980.5   51.58    4992   46.99    4996   44.03  5003.1   43.79
    5022   52.44  5070.5   53.79  5135.3   52.83  5254.2   53.53  5290.4   52.18
  5476.3   52.88  5596.3   51.48  5784.3   53.45  6107.3   54.18  6225.6   53.25
  6557.3   54.38  6647.3   53.48  6708.3   54.95  6808.5    55.6  6931.6   56.88
#Mann= 8 , 1 , 0
  3494.8      .2       0  3711.7      .1       0  4980.5     .05       0
    5022      .1       0  5784.3     .14       0  6225.6      .1       0
  6708.3     .14       0  6808.5      .2       0
#XS Ineff= 2 , 0
       0  4971.1    53.5  5030.8       0      54
Permanent Ineff=
       F       F
Bank Sta=4980.5,5022
XS Rating Curve= 0
Exp/Cntr=.5,.3

Type RM Length L Ch R = 1 ,10856.2 ,838.7,781.7,546.9
BEGIN DESCRIPTION:
Cross Section 10856.2-Interpolated
END DESCRIPTION:
XS GIS Cut Line= 6
      3154465.29     13890621.48      3154513.41     13889426.38
       3154522.3     13889230.75      3154513.41     13887923.57
      3154460.21     13887777.48      3154463.73     13887488.08
#Sta/Elev= 30
  3715.7    55.7  3765.7    55.4  3795.7    54.1  3855.7    54.2  3895.7    52.9
  3905.7    53.4  4015.7    52.7  4635.7      53  4645.7    52.6  4695.7    53.8
  4715.7    53.5  4735.7    52.2  4755.7    52.1  4795.7    53.8  4825.7    53.8
  4845.7    52.9  4977.6   52.57  4997.4   43.72  5000.6   43.49    5003   43.73
  5004.2   44.75  5024.3   52.74  5051.7    53.5  5227.6    52.4  5257.6    53.7
  5287.6    53.8  5307.6    52.4  5391.6   53.05  6734.8    53.9  6859.7      56
#Mann= 5 , 1 , 0
  3715.7      .1       0  4977.6     .04       0  5024.3      .1       0
  5391.6     .14       0  6859.7      .2       0
Bank Sta=4977.6,5024.3
XS Rating Curve= 0
Exp/Cntr=.3,.1

Type RM Length L Ch R = 1 ,10074.5 ,598.6,664.5,312.3
BEGIN DESCRIPTION:
Cross Section 10074.5
END DESCRIPTION:
XS GIS Cut Line= 6
        3155246.     13890802.57      3155294.59     13889442.98
      3155304.05     13889269.56      3155244.15     13889111.92
        3154545.     13887815.45      3154532.83      13887438.6
#Sta/Elev= 30
  3569.6      56  3574.6   52.03  3748.3    51.5  3918.3    51.4  4128.3   53.04
  4238.3   53.33  4668.3   52.09  4925.4   52.68  4977.6   51.54  4997.4   42.69
  5000.6   42.46    5003    42.7  5004.2   43.72  5024.3   51.71    5044   52.03
  5050.1    53.1  5060.1   53.17  5070.1   52.42  5103.7   52.38  5113.7   52.99
  5272.4    54.3    5432   52.91  5862.4   53.22  6072.4   52.72  6362.4   53.02
  6382.4   53.78  6562.4      54  6752.4   53.32  7032.4   54.66  7122.4   56.45
#Mann= 5 , 1 , 0
  3569.6     .14       0  4925.4      .1       0  4977.6     .05       0
  5024.3      .1       0    5432     .14       0
#XS Ineff= 2 , 0
       0  4238.3   53.33               0
Permanent Ineff=
       F       F
Bank Sta=4977.6,5024.3
XS Rating Curve= 0
Exp/Cntr=.3,.1

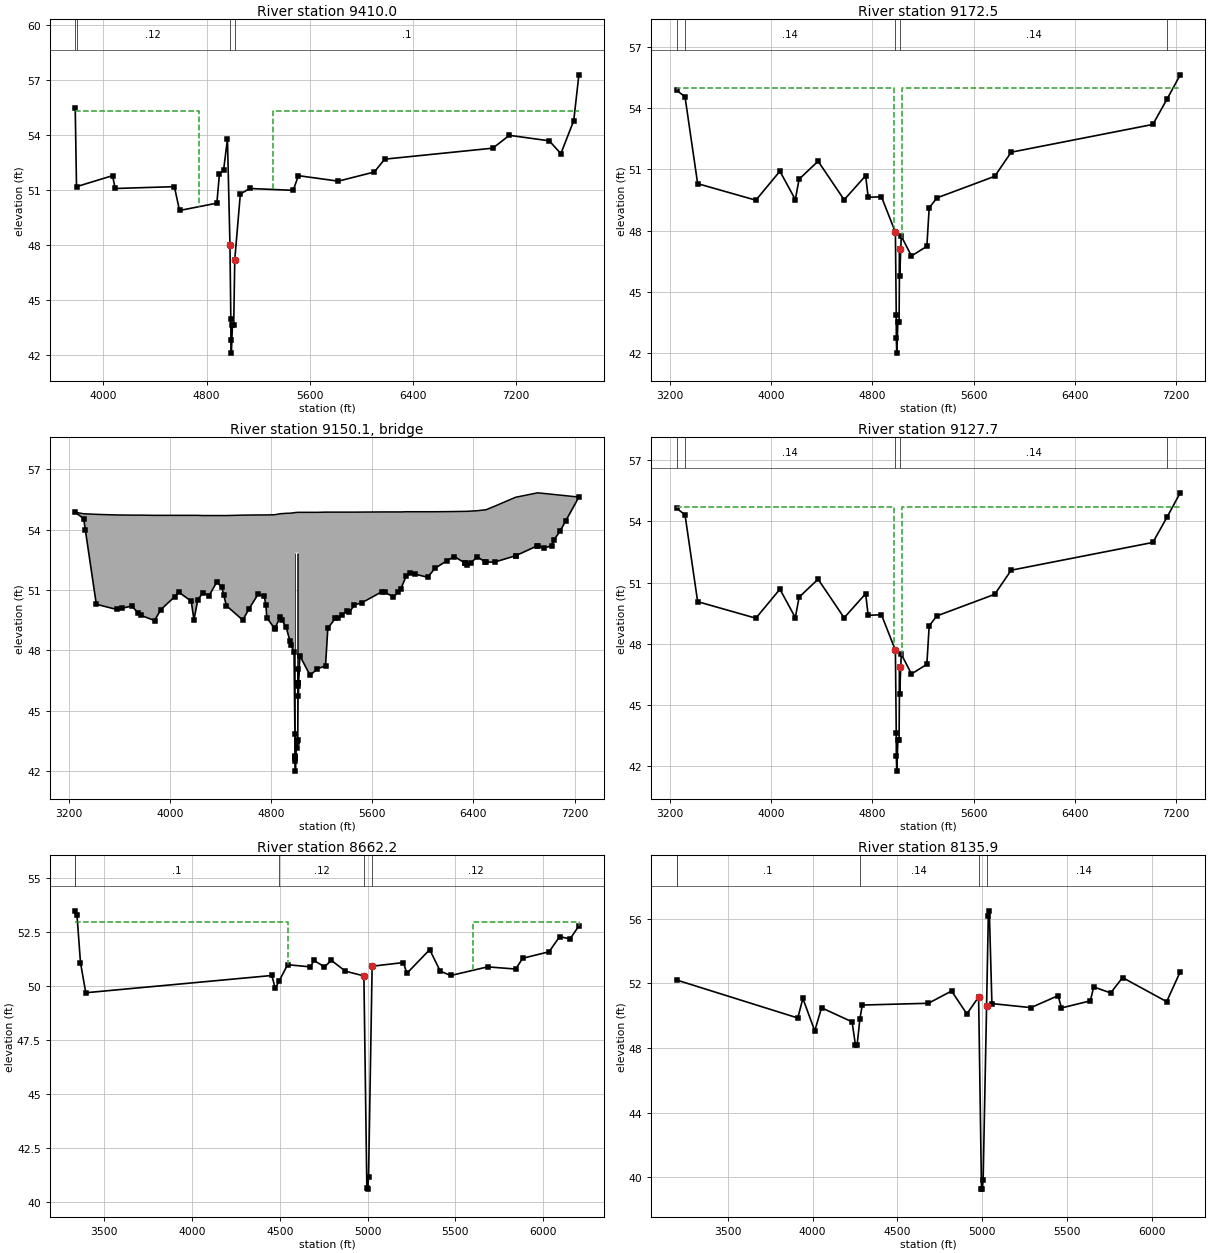
Type RM Length L Ch R = 1 ,9410.0  ,660.4,237.5,94.3
BEGIN DESCRIPTION:
Cross Section 9410.0-Interpolated
END DESCRIPTION:
XS GIS Cut Line= 6
      3155819.89     13890841.31      3155909.52     13889488.63
      3155793.92       13889293.      3154673.48     13887976.92
       3154602.9     13887854.45      3154605.93     13887395.79
#Sta/Elev= 30
  3780.5    55.5  3790.5    51.2  4070.5    51.8  4090.5    51.1  4550.5    51.2
  4590.5    49.9  4880.5    50.3  4900.5    51.9  4932.7    52.1  4962.7    53.8
  4982.1   48.04  4988.9   43.99  4989.4   42.86  4992.9   42.12  5001.5   43.63
  5011.2   43.66  5019.5   47.22  5062.7    50.8  5136.3    51.1  5473.5      51
  5513.5    51.8  5823.5    51.5  6103.5      52  6183.5    52.7  7023.5    53.3
  7151.9      54  7461.9    53.7  7551.9      53  7651.9    54.8  7691.9    57.3
#Mann= 4 , 1 , 0
  3780.5      .2       0  3790.5     .12       0  4982.1    .045       0
  5019.5      .1       0
#XS Ineff= 2 , 0
       0    4745    55.3    5320       0    55.3
Permanent Ineff=
       F       F
Bank Sta=4982.1,5019.5
XS Rating Curve= 0
Exp/Cntr=.5,.3

Type RM Length L Ch R = 1 ,9172.5  ,44.8,44.8,44.8
BEGIN DESCRIPTION:
Upstream Section of Bridge/Culvert/Weir
END DESCRIPTION:
XS GIS Cut Line= 5
      3157254.72      13890903.8      3156577.38     13890098.01
      3156308.26     13889771.93      3155663.15     13889002.11
      3154694.65     13887856.73
#Sta/Elev= 30
    3253   54.87  3319.6   54.56  3419.6    50.3  3879.6   49.49  4069.6   50.91
  4191.3   49.52  4221.3   50.52  4371.3    51.4  4577.1   49.51  4747.1   50.69
  4767.1   49.63  4871.9   49.66  4982.1   47.92  4988.9   43.87  4989.4   42.74
  4992.9      42  5001.5   43.51  5011.2   43.54  5015.5    47.1    5016   45.76
  5028.5   47.73    5109   46.76  5230.7   47.23  5249.1   49.11  5309.1    49.6
    5767   50.66    5897   51.84  7016.5    53.2  7130.3   54.46  7232.8   55.63
#Mann= 5 , 1 , 0
    3253      .2       0  3319.6     .14       0  4982.1     .04       0
  5015.5     .14       0  7130.3      .2       0
#XS Ineff= 2 , 0
       0    4970      55    5036       0      55
Permanent Ineff=
       F       F
Bank Sta=4982.1,5015.5
XS Rating Curve= 0
Exp/Cntr=.5,.3

Type RM Length L Ch R = 3 ,9150.1  ,,,
BEGIN DESCRIPTION:
UNION PACIFIC RAILROAD
Structure ID: P26-1
END DESCRIPTION:
Bridge Culvert--1,0,-1,-1, 0
Deck Dist Width WeirC Skew NumUp NumDn MinLoCord MaxHiCord MaxSubmerge Is_Ogee
10,24.8,2.6,0, 60, 60, , , .95, 0, 1,1,,
    3253  3319.6  3419.6  3579.6  3699.6  3769.6  3879.6  3929.6  4069.6  4169.6
  4191.3  4221.3  4261.3  4311.3  4371.3  4411.3  4447.1  4577.1  4697.1  4747.1
  4759.7  4767.1  4829.6  4871.9  4919.9  4958.7  4982.1  4988.9  4989.4 4989.61
  4989.7 5016.49  5016.6  5028.5    5109  5165.9  5230.7  5249.1  5309.1  5329.1
  5399.1  5419.1  5459.1  5679.1    5767    5827    5867    5897    6037    6097
  6249.2  6349.2  6429.2  6499.2  6569.2  6732.8  6906.5  6956.5  7016.5  7232.8
   54.86   54.79   54.76   54.73   54.72   54.72   54.71   54.71   54.71   54.71
   54.71   54.71    54.7    54.7    54.7    54.7    54.7   54.72   54.73   54.73
   54.73   54.73   54.74   54.79   54.81   54.82   54.84   54.85   54.85   54.85
   54.85   54.86   54.86   54.86   54.86   54.86   54.87   54.87   54.87   54.87
   54.87   54.87   54.87   54.88   54.88   54.88   54.89   54.89   54.89   54.89
    54.9   54.91   54.94   54.99   55.17   55.61   55.83    55.8   55.76   55.62
   54.86   54.55   50.29   50.03    50.2   49.74   49.48   50.02    50.9   50.44
   49.51   50.51   50.86   50.72   51.39   51.14   50.22    49.5   50.78   50.68
   50.24   49.62   49.07   49.65   49.15   48.25   47.91   43.86   42.73   42.67
   52.85   52.86   46.38   47.72   46.75   47.08   47.22    49.1   49.59   49.59
   49.94    49.9   50.25   50.92   50.65   51.07   51.67   51.83   51.63   52.08
   52.66   52.22   52.64   52.38   52.39    52.7    53.2   53.09   53.19   55.62
    3253  3319.6  3419.6  3579.6  3699.6  3769.6  3879.6  3929.6  4069.6  4169.6
  4191.3  4221.3  4261.3  4311.3  4371.3  4411.3  4447.1  4577.1  4697.1  4747.1
  4759.7  4767.1  4829.6  4871.9  4919.9  4958.7  4982.1  4988.9  4989.4 4989.61
  4989.7 5016.49  5016.6  5028.5    5109  5165.9  5230.7  5249.1  5309.1  5329.1
  5399.1  5419.1  5459.1  5679.1    5767    5827    5867    5897    6037    6097
  6249.2  6349.2  6429.2  6499.2  6569.2  6732.8  6906.5  6956.5  7016.5  7232.8
   54.86   54.79   54.76   54.73   54.72   54.72   54.71   54.71   54.71   54.71
   54.71   54.71    54.7    54.7    54.7    54.7    54.7   54.72   54.73   54.73
   54.73   54.73   54.74   54.79   54.81   54.82   54.84   54.85   54.85   54.85
   54.85   54.86   54.86   54.86   54.86   54.86   54.87   54.87   54.87   54.87
   54.87   54.87   54.87   54.88   54.88   54.88   54.89   54.89   54.89   54.89
    54.9   54.91   54.94   54.99   55.17   55.61   55.83    55.8   55.76   55.62
   54.67   54.36    50.1   49.84   50.01   49.55   49.29   49.83   50.71   50.25
   49.32   50.32   50.67   50.53    51.2   50.95   50.03   49.31   50.59   50.49
   50.05   49.43   48.88   49.46   48.96   48.06   47.72   43.67   42.54   42.48
   52.66   52.67   46.19   47.53   46.56   46.89   47.03   48.91    49.4    49.4
   49.75   49.71   50.06   50.73   50.46   50.88   51.48   51.64   51.44   51.89
   52.47   52.03   52.45   52.19    52.2   52.51   53.01    52.9      53   55.43
Pier Skew, UpSta & Num, DnSta & Num=  ,4990.3, 2 ,4990.3, 2 , 0 , 0 , 0 ,,
     1.1     1.1
   41.38   53.85
     1.1     1.1
   41.19   53.66
Pier Skew, UpSta & Num, DnSta & Num=  ,5002.7, 2 ,5002.7, 2 , 0 , 0 , 0 ,,
     1.1     1.1
   42.47   53.86
     1.1     1.1
   42.28   53.67
Pier Skew, UpSta & Num, DnSta & Num=  ,5016, 2 ,5016, 2 , 0 , 0 , 0 ,,
     1.1     1.1
   45.38   53.86
     1.1     1.1
   45.19   53.67
BR Coef= 1 , 1 , 0 ,1.25, 0 ,,,.8,0,2,0,
WSPro=,,,, 1 ,,,, 0 ,,,, 0 ,,,,-1 ,-1 ,-1 , 0 , 0 , 0 , 0 , 0
BR U #Sta/Elev= 96
    3253   54.86  3319.6   54.55    3333   53.98  3419.6   50.29  3579.6   50.03
    3623   50.09  3699.6    50.2  3749.6   49.86  3769.6   49.74  3879.6   49.48
  3929.6   50.02  4039.6   50.67  4069.6    50.9  4169.6   50.44  4191.3   49.51
  4221.3   50.51  4261.3   50.86  4311.3   50.72  4371.3   51.39  4411.3   51.14
  4425.6   50.77  4447.1   50.22  4577.1    49.5  4627.1   50.07  4697.1   50.78
  4747.1   50.68  4759.7   50.24  4767.1   49.62  4827.7   49.09  4829.6   49.07
  4871.9   49.65  4887.2   49.49  4919.9   49.15  4949.6   48.46  4958.7   48.25
  4982.1   47.91  4988.9   43.86  4989.4   42.73 4989.61   42.67  4989.7   42.65
  4989.8   42.62  4990.3   42.48  4992.9   41.99  5001.5    43.5  5002.7   43.51
  5003.4   43.46  5008.1   43.12  5011.2   43.53  5015.5   47.09    5016   45.75
  5016.3   46.21  5016.4   46.36 5016.49   46.37  5016.6   46.38  5028.5   47.72
    5109   46.75  5165.9   47.08  5230.7   47.22  5249.1    49.1  5309.1   49.59
  5329.1   49.59  5359.1   49.75  5399.1   49.94  5419.1    49.9  5459.1   50.25
  5519.1   50.37  5679.1   50.92  5699.1   50.89    5767   50.65    5807   50.89
    5827   51.07    5867   51.67    5897   51.83    5937   51.79    6037   51.63
    6097   52.08  6189.2   52.45  6249.2   52.66  6329.2   52.35  6332.8   52.33
  6349.2   52.22  6379.2   52.35  6429.2   52.64  6492.8    52.4  6499.2   52.38
  6569.2   52.39  6732.8    52.7  6736.5   52.71  6902.8   53.19  6906.5    53.2
  6956.5   53.09  7016.5   53.19  7036.5   53.49  7086.5   53.95  7130.3   54.45
  7232.8   55.62
BR U #Mann= 5
    3253      .2  3319.6     .14  4982.1     .04  5015.5     .14  7130.3      .2
BR U Banks=4982.1,5015.5
BR D #Sta/Elev= 96
    3253   54.67  3319.6   54.36    3333   53.79  3419.6    50.1  3579.6   49.84
    3623    49.9  3699.6   50.01  3749.6   49.67  3769.6   49.55  3879.6   49.29
  3929.6   49.83  4039.6   50.48  4069.6   50.71  4169.6   50.25  4191.3   49.32
  4221.3   50.32  4261.3   50.67  4311.3   50.53  4371.3    51.2  4411.3   50.95
  4425.6   50.58  4447.1   50.03  4577.1   49.31  4627.1   49.88  4697.1   50.59
  4747.1   50.49  4759.7   50.05  4767.1   49.43  4827.7    48.9  4829.6   48.88
  4871.9   49.46  4887.2    49.3  4919.9   48.96  4949.6   48.27  4958.7   48.06
  4982.1   47.72  4988.9   43.67  4989.4   42.54 4989.61   42.48  4989.7   42.46
  4989.8   42.43  4990.3   42.29  4992.9    41.8  5001.5   43.31  5002.7   43.32
  5003.4   43.27  5008.1   42.93  5011.2   43.34  5015.5    46.9    5016   45.56
  5016.3   46.02  5016.4   46.17 5016.49   46.18  5016.6   46.19  5028.5   47.53
    5109   46.56  5165.9   46.89  5230.7   47.03  5249.1   48.91  5309.1    49.4
  5329.1    49.4  5359.1   49.56  5399.1   49.75  5419.1   49.71  5459.1   50.06
  5519.1   50.18  5679.1   50.73  5699.1    50.7    5767   50.46    5807    50.7
    5827   50.88    5867   51.48    5897   51.64    5937    51.6    6037   51.44
    6097   51.89  6189.2   52.26  6249.2   52.47  6329.2   52.16  6332.8   52.14
  6349.2   52.03  6379.2   52.16  6429.2   52.45  6492.8   52.21  6499.2   52.19
  6569.2    52.2  6732.8   52.51  6736.5   52.52  6902.8      53  6906.5   53.01
  6956.5    52.9  7016.5      53  7036.5    53.3  7086.5   53.76  7130.3   54.26
  7232.8   55.43
BR D #Mann= 5
    3253      .2  3319.6     .14  4982.1     .04  5015.5     .14  7130.3      .2
BR D Banks=4982.1,5015.5
BC Design=,, 0 ,, 0 ,,,,,,

Type RM Length L Ch R = 1 ,9127.7  ,465.5,465.5,465.5
BEGIN DESCRIPTION:
Downstream Section of Bridge/Culvert/Weir
END DESCRIPTION:
XS GIS Cut Line= 5
      3157288.14     13890873.96       3156610.8     13890068.17
      3156341.68     13889742.09      3155696.57     13888972.27
      3154728.07     13887826.89
#Sta/Elev= 30
    3253   54.64  3319.6   54.33  3419.6   50.07  3879.6   49.26  4069.6   50.68
  4191.3   49.29  4221.3   50.29  4371.3   51.17  4577.1   49.28  4747.1   50.46
  4767.1    49.4  4871.9   49.43  4982.1   47.69  4988.9   43.64  4989.4   42.51
  4992.9   41.77  5001.5   43.28  5011.2   43.31  5015.5   46.87    5016   45.53
  5028.5    47.5    5109   46.53  5230.7      47  5249.1   48.88  5309.1   49.37
    5767   50.43    5897   51.61  7016.5   52.97  7130.3   54.23  7232.8    55.4
#Mann= 5 , 1 , 0
    3253      .2       0  3319.6     .14       0  4982.1     .04       0
  5015.5     .14       0  7130.3      .2       0
#XS Ineff= 2 , 0
       0    4970    54.7    5036       0    54.7
Permanent Ineff=
       F       F
Bank Sta=4982.1,5015.5
XS Rating Curve= 0
Exp/Cntr=.5,.3

Type RM Length L Ch R = 1 ,8662.2  ,624.7,526.3,370
BEGIN DESCRIPTION:
Cross Section 8662.2-Interpolated
END DESCRIPTION:
XS GIS Cut Line= 4
      3157341.19     13890884.73      3156594.23     13889630.91
      3156585.34     13889310.78       3155721.1      13888646.6
#Sta/Elev= 30
  3333.9    53.5  3343.9    53.3  3363.9    51.1  3393.9    49.7  4453.9    50.5
  4473.9    49.9  4494.7   50.23  4543.9      51  4673.9    50.9  4693.9    51.2
  4753.9    50.9  4793.4    51.2  4873.4    50.7  4978.6   50.48  4995.5   40.62
  5000.7   40.59  5005.2   41.16  5025.6   50.93  5203.6    51.1  5223.6    50.6
  5353.6    51.7  5413.6    50.7  5473.6    50.5  5683.6    50.9  5843.6    50.8
  5883.6    51.3  6033.6    51.6  6093.6    52.3  6153.6    52.2  6203.6    52.8
#Mann= 5 , 1 , 0
  3333.9      .2       0  3333.9      .1       0  4494.7     .12       0
  4978.6     .04       0  5025.6     .12       0
#XS Ineff= 2 , 0
       0  4544.4      53  5600.4       0      53
Permanent Ineff=
       F       F
Bank Sta=4978.6,5025.6
XS Rating Curve= 0
Exp/Cntr=.3,.1

Type RM Length L Ch R = 1 ,8135.9  ,889.6,892.7,1049.4
BEGIN DESCRIPTION:
Cross Section 8135.9
END DESCRIPTION:
XS GIS Cut Line= 5
      3157812.96     13890909.29      3157776.38     13890396.08
      3157192.43     13889456.17      3157048.71     13889266.88
       3156067.2     13888748.31
#Sta/Elev= 30
  3198.2    52.2  3912.7   49.85  3942.7   51.06  4012.7   49.05  4052.7   50.48
  4232.7   49.61  4252.7   48.17  4262.7    48.2  4278.6   49.77  4292.7   50.65
  4682.7   50.76  4819.3   51.52  4909.3    50.1  4978.6   51.15  4995.5   39.29
  5000.7   39.26  5005.2   39.83  5025.6    50.6  5035.7   56.16  5041.6   56.48
    5057   50.74    5287   50.49    5447   51.23    5467   50.47    5637   50.91
    5657   51.77    5757    51.4    5827   52.35    6087   50.86    6167   52.71
#Mann= 5 , 1 , 0
  3198.2      .2       0  3198.2      .1       0  4278.6     .14       0
  4978.6     .04       0  5025.6     .14       0
#XS Ineff= 2 , 0
       0  4698.7    50.8    5827       0   52.35
Permanent Ineff=
       F       F
Bank Sta=4978.6,5025.6
XS Rating Curve= 0
Exp/Cntr=.3,.1

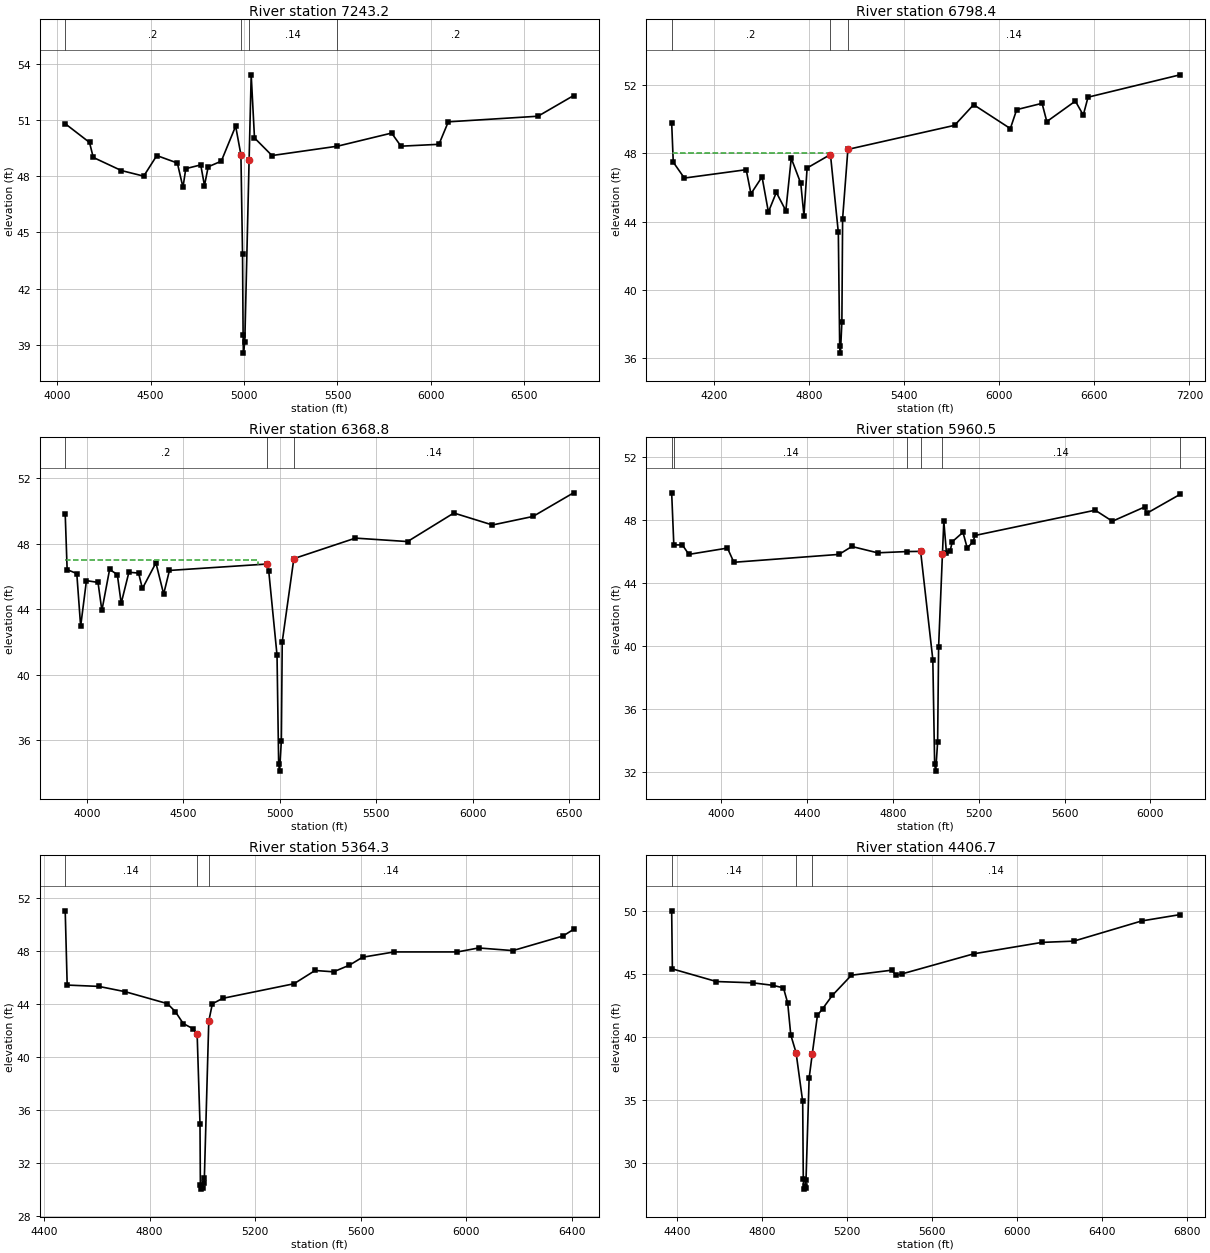
Type RM Length L Ch R = 1 ,7243.2  ,426.5,444.8,491.4
BEGIN DESCRIPTION:
Cross Section 7243.2
END DESCRIPTION:
XS GIS Cut Line= 5
      3158012.68     13889764.64      3158016.19     13889119.66
      3157812.88     13888797.16      3157171.94     13888280.55
      3156347.94     13888001.56
#Sta/Elev= 30
  4043.4    50.8  4173.4    49.8  4193.4      49  4343.4    48.3  4463.4      48
  4533.4    49.1  4643.4    48.7  4673.4    47.4  4688.4    48.4  4768.4    48.6
  4788.4    47.5  4808.4    48.5  4878.4    48.8  4955.2   50.67  4983.4   49.14
  4992.1   43.82  4995.1   39.53  4996.5   38.55  5004.1   39.13  5027.2   48.87
  5038.4   53.41    5056   50.04  5149.6    49.1    5500    49.6  5789.6    50.3
  5839.6    49.6  6042.8    49.7  6092.8    50.9  6572.8    51.2  6762.8    52.3
#Mann= 4 , 1 , 0
  4043.4      .2       0  4983.4    .045       0  5027.2     .14       0
    5500      .2       0
#XS Ineff= 2 , 0
       0  4878.2      48    5056       0   50.04
Permanent Ineff=
       F       F
Bank Sta=4983.4,5027.2
XS Rating Curve= 0
Exp/Cntr=.3,.1

Type RM Length L Ch R = 1 ,6798.4  ,494.6,429.6,421.9
BEGIN DESCRIPTION:
Cross Section 6798.4-Interpolated
END DESCRIPTION:
XS GIS Cut Line= 6
      3158481.28     13889655.23       3158375.1     13888935.56
      3158282.43     13888750.23      3158201.35     13888553.31
       3157541.1      13887939.4      3156493.11     13887449.58
#Sta/Elev= 30
  3934.4    49.8  3944.4   47.49  4014.4   46.56  4404.4   47.05  4434.4   45.64
  4504.4   46.63  4544.4   44.57  4594.4   45.72  4654.4   44.65  4688.6   47.72
  4748.6   46.25  4768.6   44.36  4788.6   47.15  4935.8   47.94  4985.5   43.37
    4994   36.72  4998.9    36.3  5007.9   38.14  5012.5   44.18  5045.8   48.24
  5718.8   49.65  5838.8   50.86  6070.4   49.46  6110.4   50.57  6270.4   50.94
  6300.4   49.87  6480.4   51.07  6530.4   50.25  6560.4    51.3  7140.4   52.61
#Mann= 3 , 1 , 0
  3934.4      .2       0  4935.8     .05       0  5045.8     .14       0
#XS Ineff= 2 , 0
       0    4935      48               0
Permanent Ineff=
       F       F
Bank Sta=4935.8,5045.8
XS Rating Curve= 0
Exp/Cntr=.3,.1

Type RM Length L Ch R = 1 ,6368.8  ,393.3,408.3,423.7
BEGIN DESCRIPTION:
Cross Section 6368.8-Interpolated
END DESCRIPTION:
XS GIS Cut Line= 4
      3158933.66     13889466.46      3158676.26      13888495.4
      3158490.93      13888286.9      3157324.38     13887607.35
#Sta/Elev= 30
  3888.1    49.8  3898.1   46.41  3948.1   46.17  3968.1   42.95  3998.1   45.74
  4058.1   45.63  4078.1   43.92  4118.1   46.42  4158.1   46.11  4178.1   44.36
  4218.1   46.25  4268.1    46.2  4288.1   45.26  4358.1   46.82  4398.1   44.92
  4428.1   46.36  4932.7   46.75  4942.7   46.31  4985.5    41.2    4994   34.55
  4998.9   34.13  5007.9   35.97  5012.5   42.01  5072.7   47.08  5391.7   48.33
  5661.7   48.12  5901.7   49.86  6101.7   49.13  6311.7   49.65  6521.7   51.09
#Mann= 3 , 1 , 0
  3888.1      .2       0  4932.7     .07       0  5072.7     .14       0
#XS Ineff= 2 , 0
       0  4887.1   47.01               0
Permanent Ineff=
       F       F
Bank Sta=4932.7,5072.7
XS Rating Curve= 0
Exp/Cntr=.3,.1

Type RM Length L Ch R = 1 ,5960.5  ,625.1,596.2,547.2
BEGIN DESCRIPTION:
Cross Section 5960.5
END DESCRIPTION:
XS GIS Cut Line= 4
      3159095.72     13889413.07      3159049.37     13888356.21
       3158865.7     13888062.35      3157965.75     13887713.39
#Sta/Elev= 30
  3768.1    49.7  3778.1    46.4  3818.1    46.4  3848.1    45.8  4028.1    46.2
  4058.1    45.3  4548.1    45.8  4608.1    46.3  4728.1    45.9  4865.6   45.98
  4928.6   45.99  4985.5   39.14    4994   32.49  4998.9   32.07  5007.9   33.91
  5012.5   39.95  5030.3   45.81  5036.8    47.9    5049   45.89    5066      46
    5076    46.6    5126    47.2    5146    46.2  5172.5    46.6  5182.5      47
  5742.5    48.6  5822.5    47.9  5972.5    48.8  5982.5    48.4  6137.8    49.6
#Mann= 6 , 1 , 0
  3768.1      .2       0  3778.1     .14       0  4865.6      .1       0
  4928.6     .07       0  5030.3     .14       0  6137.8      .2       0
#XS Ineff= 2 , 0
       0                  5036.8       0    47.9
Permanent Ineff=
       F       F
Bank Sta=4928.6,5030.3
XS Rating Curve= 0
Exp/Cntr=.3,.1

Type RM Length L Ch R = 1 ,5364.3  ,944.3,957.6,974.8
BEGIN DESCRIPTION:
Cross Section 5364.3
END DESCRIPTION:
XS GIS Cut Line= 2
      3159882.43     13887921.16      3157971.57      13887668.4
#Sta/Elev= 29
    4480      51  4487.5    45.4  4607.5    45.3  4707.5    44.9  4867.5      44
  4897.5    43.4  4927.5    42.5  4965.3    42.1  4980.3    41.7  4991.1   34.92
  4992.5   30.35  4993.7   30.01  5000.7   30.08  5005.3   30.48  5007.6   30.82
  5024.4   42.68    5038   43.99  5077.5    44.4  5347.5    45.5  5427.5    46.5
  5497.5    46.4  5557.5    46.9  5607.5    47.5  5727.5    47.9  5967.5    47.9
  6047.5    48.2  6177.5      48  6367.5    49.1  6407.5    49.6
#Mann= 3 , 1 , 0
    4480     .14       0  4980.3     .06       0  5024.4     .14       0
Bank Sta=4980.3,5024.4
XS Rating Curve= 0
Exp/Cntr=.3,.1

Type RM Length L Ch R = 1 ,4406.7  ,0,0,0
BEGIN DESCRIPTION:
Cross Section 4406.7
END DESCRIPTION:
XS GIS Cut Line= 5
      3159915.15     13887122.85      3159833.58     13887122.75
      3159493.02     13886941.83      3158907.67     13886899.26
      3157570.21     13886835.13
#Sta/Elev= 29
  4373.9      50  4377.2    45.4  4584.5    44.4  4754.5    44.3  4850.1    44.1
  4900.1    43.9  4920.1    42.7  4934.6   40.17  4959.5   38.77  4990.7    34.9
  4993.5   28.73  4996.1   27.96  5001.4   28.17  5004.3   28.04  5006.4   28.72
    5021   36.75  5035.8   38.67  5060.2   41.73  5084.3   42.24  5130.1    43.3
  5220.1    44.9  5410.1    45.3  5430.1    44.9    5457      45    5797    46.6
    6117    47.5    6267    47.6    6587    49.2    6767    49.7
#Mann= 3 , 1 , 0
  4373.9     .14       0  4959.5     .06       0  5035.8     .14       0
Bank Sta=4959.5,5035.8
XS Rating Curve= 0
Exp/Cntr=.3,.1

Chan Stop Cuts=-1